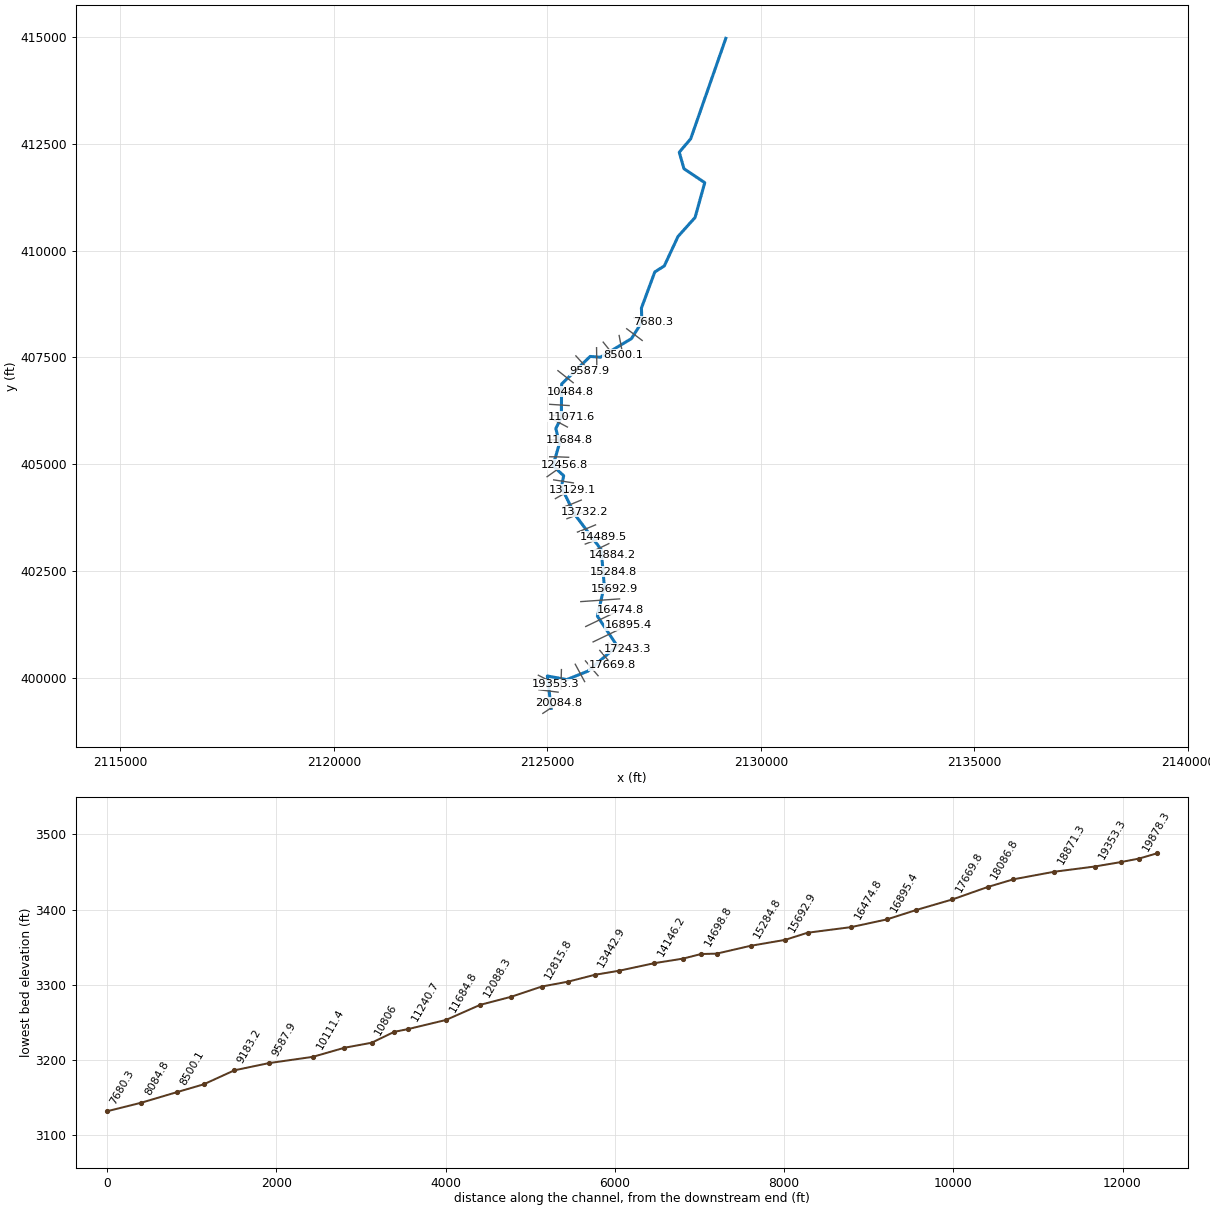
--- CldKnobFrk.prj (project) ---

Proj Title=CldKnobFrk
Current Plan=p01
Default Exp/Contr=0,0
English Units
Geom File=g01
Flow File=f01
Plan File=p01
BEGIN DESCRIPTION:
END DESCRIPTION:
DSS Export Rating Curves= 0
DSS Export Rating Curve Sorted= 0
DSS Export Volume Flow Curves= 0
DXF OffsetX= 0
DXF OffsetY= 0
DXF ScaleX= 0
DXF ScaleY= 0

--- CldKnobFrk.p01 (plan) ---

Plan Title=Floodplain
Program Version=4.00
Geom File=g01
Flow File=f01
K Sum by GR=0
Std Step Tol=0.01
Critical Tol=0.01
Num of Std Step Trials=20
Max Error Tol=0.3
Flow Tol Ratio=0.001
Split Flow NTrial=30
Split Flow Tol=0.02
Split Flow Ratio=0.02
Log Output Level=0
Friction Slope Method=1
Unsteady Friction Slope Method=2
Unsteady Bridges Friction Slope Method=1
Global Log Level=0
CheckData=False
Run HTab=0
Run UNet=0
Run PostProcess=0
UNET Theta=0
UNET Theta Warmup=0
UNET ZTol=0
UNET ZSATol=0
UNET MxIter=0
UNET MaxInSteps=0
UNET DtIC=0
UNET DtMin=0
UNET MaxCRTS=0
UNET WFStab=0
UNET SFStab=0
UNET WFX=0
UNET SFX=0
UNET DSS MLevel=0
UNET DZMax Abort=0
UNET Convert EG Bridges=0
UNET Use Existing IB Tables=0
UNET Froude Limit=0
UNET Froude Power=0
Write IC File=0
Echo Input=False
Echo Output=False
Write Detailed=0

--- CldKnobFrk.f01 (steady flow) ---

Flow Title=NFF Regression Equation
Program Version=4.00
Number of Profiles=1
Profile Names=P100yr
River Rch & RM=CldKnobFrk,Main      ,20084.8
517.1070
River Rch & RM=CldKnobFrk,Main      ,19353.3
521.2398
River Rch & RM=CldKnobFrk,Main      ,18871.3
598.3089
River Rch & RM=CldKnobFrk,Main      ,17669.8
612.2292
River Rch & RM=CldKnobFrk,Main      ,16895.4
762.5409
River Rch & RM=CldKnobFrk,Main      ,15957.8
779.3878
River Rch & RM=CldKnobFrk,Main      ,14146.2
858.6764
River Rch & RM=CldKnobFrk,Main      ,10111.4
946.8564
River Rch & RM=CldKnobFrk,Main      ,9587.9
1281.707
River Rch & RM=CldKnobFrk,Main      ,7205.7
1416.797
River Rch & RM=CldKnobFrk,Main      ,4886.1
1564.439
River Rch & RM=CldKnobFrk,Main      ,288.3
1719.402
Boundary for River Rch & Prof#=CldKnobFrk,Main      ,1
Up Type=0
Dn Type=3
Dn Slope=0.023601

--- CldKnobFrk.g01 (geometry) ---

Geom Title=USGS 10m DEM
Program Version=4.00

River Reach=CldKnobFrk      ,Main
Reach XY= 30
     2125090.076      399281.414     2125000.232      400039.226
     2125454.763      399954.541     2125946.883      400151.389
     2126635.851      400741.933     2126172.867      401438.966
     2126333.683      402150.113     2126260.537      402998.548
     2125648.303      403814.491     2125327.324      404457.344
      2125382.86      404727.688     2125131.377      404958.214
     2125284.363      405488.422     2125198.439      405835.259
     2125328.372      406094.076     2125334.659      406875.767
     2126003.183      407521.239     2126243.139      407502.378
      2126969.09       407938.49     2127212.655      408322.658
     2127203.316        408653.7     2127516.269      409499.567
     2127738.412      409639.978       2128060.1      410330.507
     2128459.328      410774.793     2128685.662      411590.015
     2128199.463      411915.894      2128089.11      412301.558
     2128356.639      412616.901     2129179.197       414969.31

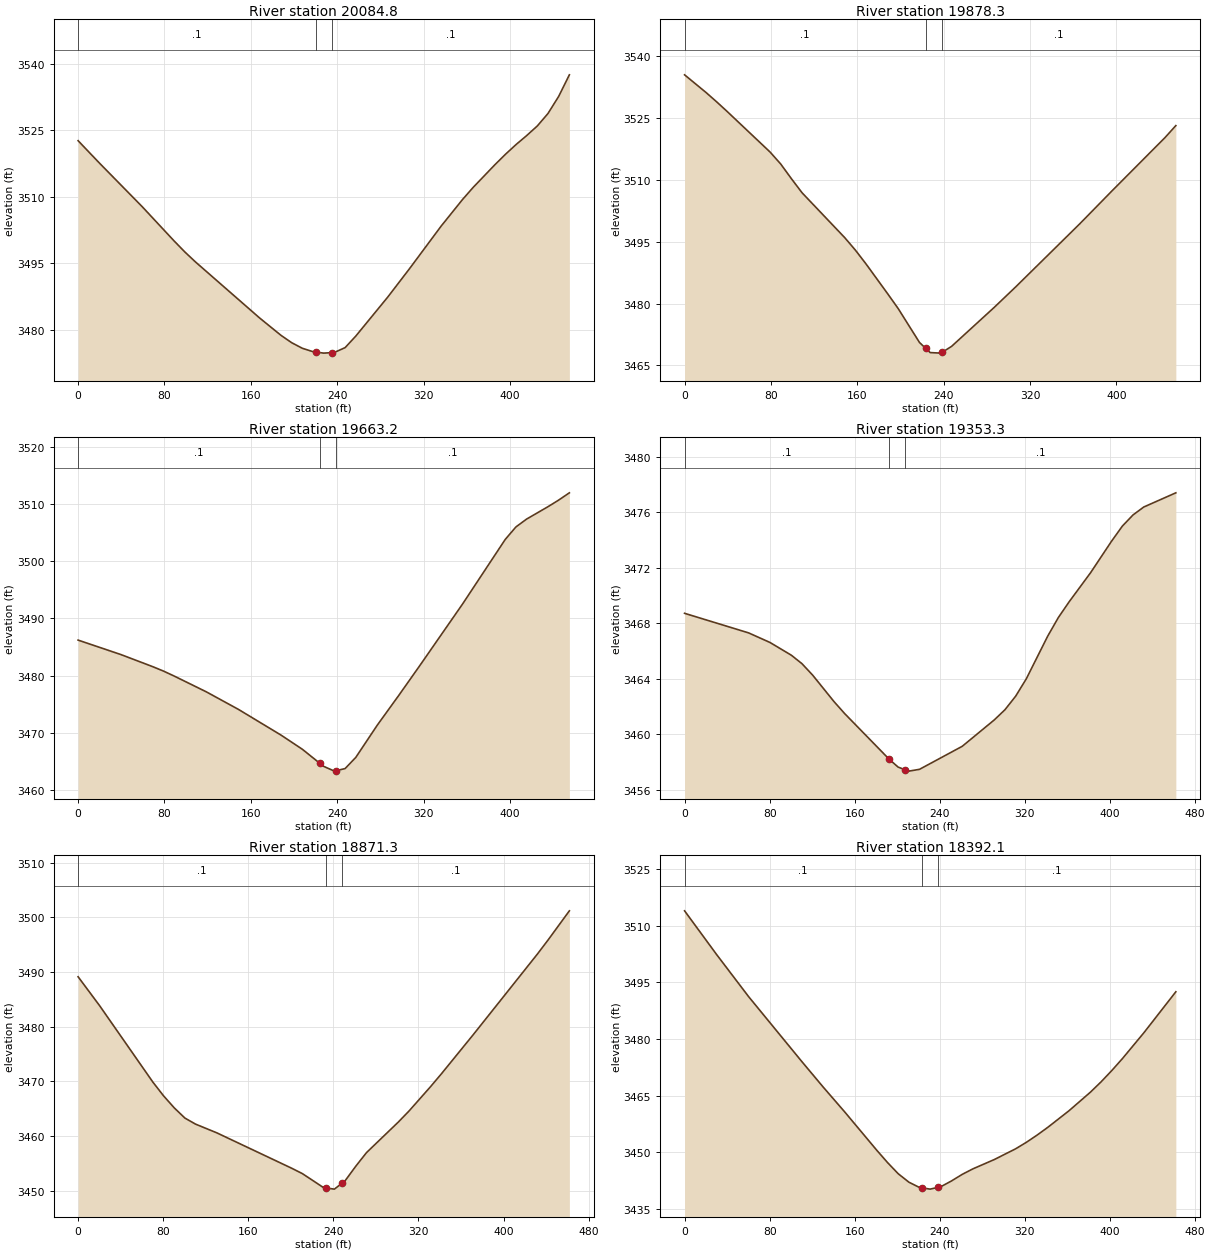
Type RM Length L Ch R = 1 ,20084.8 ,219.2,206.4,193.7
XS GIS Cut Line= 3
     2124894.976      399163.973     2125084.547      399289.747
     2125274.119       399415.52
#Sta/Elev= 30
       0 3522.63    19.8 3517.58    59.4 3507.76      89 3500.03    98.9 3497.56
   108.8  3495.3   168.2 3482.68   187.9 3478.79   197.8 3477.13   207.7 3475.87
   217.6  3475.1     220 3475.02   227.5 3474.78     235  3474.9   237.4 3474.94
   247.3 3476.02   257.2 3478.62   286.8 3487.41   306.6 3493.69   336.3 3503.41
   356.1  3509.4     366 3512.14   385.8 3517.16   395.6 3519.52   405.5 3521.74
   415.4 3523.77   425.3 3525.95   435.2 3528.76   445.1 3532.61     455 3537.47
#Mann= 3 , 0 , 0
       0      .1       0     220    .045       0     235      .1       0
Bank Sta=220,235
XS Rating Curve= 0 ,0
Exp/Cntr=0.3,0.1

Type RM Length L Ch R = 1 ,19878.3 ,218.7,215.2,211.7
XS GIS Cut Line= 2
     2124782.711      399470.471     2125237.524      399483.507
#Sta/Elev= 25
       0 3535.49    19.8 3531.22    29.7 3528.94    39.6 3526.56    79.1 3516.78
      89 3513.87    98.9 3510.31   108.8 3506.88   148.4 3495.97   158.3 3492.93
   168.2 3489.56   187.9 3482.45   197.8  3478.8   217.6 3470.55   223.4 3469.11
   227.5  3468.1   237.4 3467.97   238.4 3468.14   247.3 3469.61   286.8 3479.07
   306.6 3484.02     366 3499.34   395.6 3507.26   445.1  3520.3     455 3523.17
#Mann= 3 , 0 , 0
       0      .1       0   223.4    .045       0   238.4      .1       0
Bank Sta=223.4,238.4
XS Rating Curve= 0 ,0
Exp/Cntr=0.3,0.1

Type RM Length L Ch R = 1 ,19663.2 ,318,309.9,301.8
XS GIS Cut Line= 2
     2124800.947      399717.905     2125252.318      399660.558
#Sta/Elev= 25
       0 3486.21    39.6 3483.68    69.2 3481.55    79.1 3480.78      89 3479.91
   118.7 3477.15   148.4 3474.08   187.9 3469.57   207.7 3467.08   223.9 3464.62
   227.5 3464.08   237.4 3463.25   238.9 3463.32   247.3  3463.7   257.2 3465.66
     277 3471.28   296.7 3476.44   316.5 3481.75   356.1 3492.54   395.6 3503.85
   405.5 3506.04   415.4 3507.42   435.2 3509.59   445.1 3510.75     455 3512.02
#Mann= 3 , 0 , 0
       0      .1       0   223.9    .045       0   238.9      .1       0
Bank Sta=223.9,238.9
XS Rating Curve= 0 ,0
Exp/Cntr=0.3,0.1

Type RM Length L Ch R = 1 ,19353.3 ,509.8,482,453.6
XS GIS Cut Line= 2
     2124789.651      400057.172     2125199.823      399844.814
#Sta/Elev= 27
       0 3468.71    60.2  3467.3    80.3 3466.61   100.4 3465.69   110.4 3465.08
   120.5 3464.25   140.6 3462.34   150.6 3461.48   192.6 3458.18   200.8 3457.63
   207.6 3457.43   210.9 3457.34   220.9 3457.47   261.1 3459.13   291.2 3461.03
   301.2 3461.76   311.3 3462.74   321.3 3463.99   341.4 3467.06   351.4  3468.4
   361.5 3469.53   381.6 3471.62   401.6 3473.92   411.7    3475   421.7  3475.8
   431.8 3476.37   461.9 3477.39
#Mann= 3 , 0 , 0
       0      .1       0   192.6    .045       0   207.6      .1       0
Bank Sta=192.6,207.6
XS Rating Curve= 0 ,0
Exp/Cntr=0.3,0.1

Type RM Length L Ch R = 1 ,18871.3 ,467.2,479.2,491.2
XS GIS Cut Line= 2
     2125329.976      400189.188     2125318.065      399727.458
#Sta/Elev= 25
       0 3489.13    20.1 3483.88    70.3 3469.88    80.3 3467.38    90.4 3465.17
   100.4 3463.31   110.4  3462.2   130.5  3460.6   200.8 3454.14   210.9 3453.15
   230.9 3450.58   233.3 3450.52     241 3450.32   248.3 3451.43     251 3451.84
   261.1 3454.51   271.1 3456.98   301.2  3462.6   311.3 3464.63   331.4 3469.05
   341.4 3471.35   371.5 3478.54   431.8 3493.27   441.8 3495.83   461.9 3501.18
#Mann= 3 , 0 , 0
       0      .1       0   233.3    .045       0   248.3      .1       0
Bank Sta=233.3,248.3
XS Rating Curve= 0 ,0
Exp/Cntr=0.3,0.1

Type RM Length L Ch R = 1 ,18392.1 ,300.6,305.3,310
XS GIS Cut Line= 2
     2125653.899      400314.461     2125873.283      399908.003
#Sta/Elev= 30
       0  3513.9    30.1 3502.35    60.2 3491.21   110.4 3473.98   130.5 3467.23
   150.6  3460.7   180.7 3450.58   190.8 3447.33   200.8 3444.38   210.9 3442.13
   220.9 3440.72     223 3440.63   230.9 3440.29     238 3440.75     241 3440.94
     251 3442.46   261.1  3444.2   271.1 3445.65   291.2 3448.11   311.3 3450.96
   321.3 3452.66   331.4 3454.57   341.4 3456.61   361.5 3461.03   381.6 3465.94
   391.6 3468.66   401.6 3471.63   411.7 3474.82   431.8 3481.63   461.9 3492.49
#Mann= 3 , 0 , 0
       0      .1       0     223    .045       0     238      .1       0
Bank Sta=223,238
XS Rating Curve= 0 ,0
Exp/Cntr=0.3,0.1

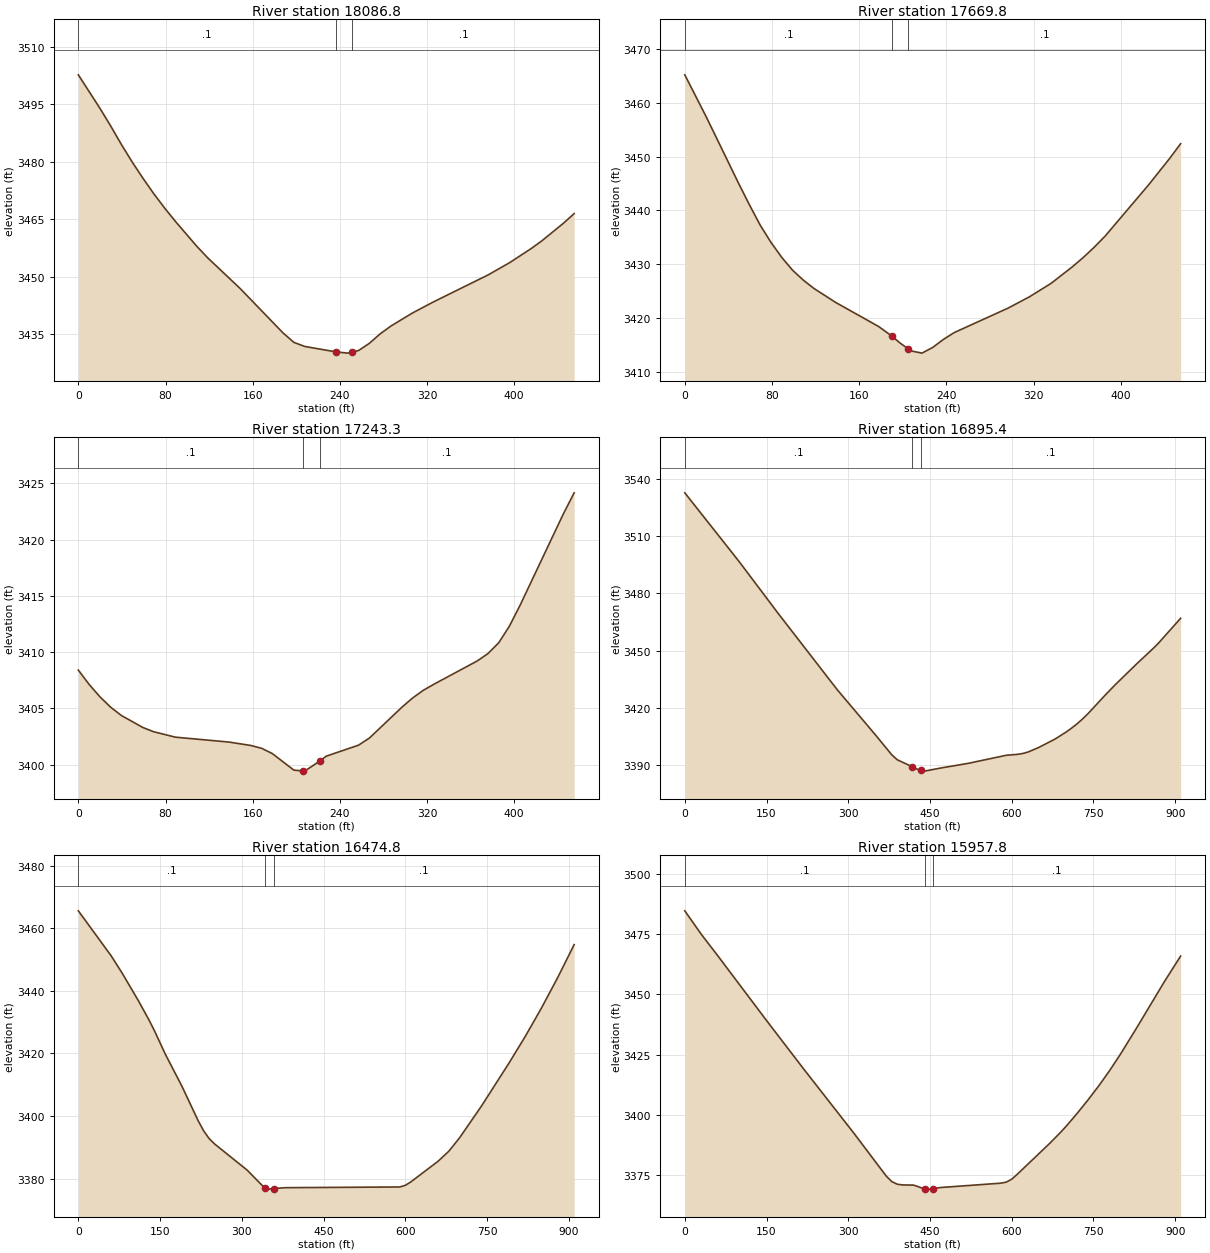
Type RM Length L Ch R = 1 ,18086.8 ,416.9,416.9,416.9
XS GIS Cut Line= 2
     2125892.424      400392.179     2126187.608      400045.926
#Sta/Elev= 30
       0 3502.68    19.8 3493.95    29.7 3489.32    39.6 3484.45    49.5 3479.88
    59.4 3475.64    69.2 3471.65    79.1 3467.93      89 3464.44   108.8 3457.88
   118.7  3454.9   148.4 3446.91   187.9 3435.27   197.8 3432.82   207.7 3431.76
   236.5 3430.33   247.3 3430.01   251.5  3430.3   257.2 3430.69   267.1 3432.57
     277 3435.05   286.8 3437.07   306.6 3440.49   326.4 3443.46   375.9 3450.41
   395.6  3453.6   415.4 3457.28   425.3 3459.32   445.1 3463.91     455 3466.44
#Mann= 3 , 0 , 0
       0      .1       0   236.5    .045       0   251.5      .1       0
Bank Sta=236.5,251.5
XS Rating Curve= 0 ,0
Exp/Cntr=0.3,0.1

Type RM Length L Ch R = 1 ,17669.8 ,413.7,426.6,440.9
XS GIS Cut Line= 3
     2126227.702      400638.447     2126375.294      400465.321
     2126522.887      400292.194
#Sta/Elev= 30
       0 3465.25    19.8 3457.38    49.5    3445    59.4 3441.02    69.2 3437.27
    79.1 3434.06      89 3431.26    98.9 3428.88   108.8 3427.03   118.7 3425.46
   138.5 3422.88     178 3418.39   189.9 3416.64   197.8 3415.29   204.9 3414.27
   207.7 3413.86   217.6 3413.45   227.5 3414.51   237.4 3416.01   247.3 3417.28
   296.7 3421.83   316.5 3423.96   336.3 3426.46   356.1 3429.59     366 3431.31
   375.9  3433.2   385.8 3435.25   425.3 3444.69   445.1 3449.73     455 3452.43
#Mann= 3 , 0 , 0
       0      .1       0   189.9    .045       0   204.9      .1       0
Bank Sta=189.9,204.9
XS Rating Curve= 0 ,0
Exp/Cntr=0.3,0.1

Type RM Length L Ch R = 1 ,17243.3 ,330.6,347.9,363.5
XS GIS Cut Line= 2
     2126429.882      400799.913     2126867.742      400676.204
#Sta/Elev= 30
       0  3408.4     9.9 3407.13    19.8 3406.03    29.7  3405.1    39.6 3404.36
    59.4 3403.29    69.2 3402.92      89 3402.44   138.5    3402   158.3  3401.7
   168.2 3401.45     178 3400.98   197.8 3399.51   206.5 3399.43   207.7 3399.42
   221.5 3400.31   227.5 3400.75   257.2 3401.73   267.1 3402.36   296.7 3405.08
   306.6 3405.91   316.5  3406.6   326.4 3407.15     366 3409.21   375.9 3409.87
   385.8 3410.83   395.6 3412.31   405.5 3414.19   445.1 3422.29     455 3424.16
#Mann= 3 , 0 , 0
       0      .1       0   206.5    .045       0   221.5      .1       0
Bank Sta=206.5,221.5
XS Rating Curve= 0 ,0
Exp/Cntr=0.3,0.1

Type RM Length L Ch R = 1 ,16895.4 ,420.2,420.6,421
XS GIS Cut Line= 2
      2126072.06      400837.119      2126892.32      401230.844
#Sta/Elev= 30
       0 3532.62     100 3496.51     170 3469.96     280 3429.41     350 3405.78
   379.9 3395.38   389.9  3392.8   417.7 3389.11   429.9 3387.42   432.7 3387.26
   439.9 3386.85   469.9 3388.49   519.9 3390.91   589.9 3395.15   609.9 3395.62
   619.9 3396.06   629.9 3396.85   649.9 3399.29   679.9 3403.72   699.9 3407.34
   709.9  3409.4   719.9 3411.63   729.9 3414.16   739.9 3416.93   769.9 3426.19
   789.9 3432.11   829.9  3443.2   859.9  3451.2   869.9 3454.09   909.9  3466.9
#Mann= 3 , 0 , 0
       0      .1       0   417.7    .045       0   432.7      .1       0
Bank Sta=417.7,432.7
XS Rating Curve= 0 ,0
Exp/Cntr=0.3,0.1

Type RM Length L Ch R = 1 ,16474.8 ,527.3,517,506.5
XS GIS Cut Line= 2
     2125898.967      401197.728     2126719.228      401591.453
#Sta/Elev= 30
       0 3465.59      60 3451.27      80  3445.8     110 3436.92     130  3430.6
     140 3427.14     160 3419.64     190 3409.56     220 3398.47     230 3395.26
     240 3392.79     250 3391.08     310 3382.68     340 3377.34   343.4  3377.1
     350 3376.63   358.4 3376.82   379.9 3377.09   589.9 3377.32   599.9 3377.83
   609.9  3378.9   659.9  3385.5   679.9 3388.74   699.9 3393.09   739.9 3403.21
   789.9  3416.8   819.9 3425.36   849.9 3434.52   879.9 3444.32   909.9 3454.79
#Mann= 3 , 0 , 0
       0      .1       0   343.4    .045       0   358.4      .1       0
Bank Sta=343.4,358.4
XS Rating Curve= 0 ,0
Exp/Cntr=0.3,0.1

Type RM Length L Ch R = 1 ,15957.8 ,265,264.8,264.6
XS GIS Cut Line= 2
     2125783.656       401780.69     2126691.283      401844.408
#Sta/Elev= 30
       0 3484.69      30 3475.02      60 3466.19     150 3439.13     220 3418.46
     310 3392.41   369.9 3374.46   379.9 3372.22   389.9 3371.13   399.9 3370.83
   419.9 3370.76   440.7 3369.14   449.9 3369.09   455.7 3369.31   469.9 3369.77
   579.9 3371.56   589.9 3371.99   599.9 3373.21   609.9 3375.21   669.9 3388.15
   689.9 3392.75   699.9 3395.21   719.9 3400.52   739.9 3406.13   759.9 3412.05
   779.9 3418.43   799.9 3425.29   829.9 3436.32   879.9  3455.2   909.9 3465.89
#Mann= 3 , 0 , 0
       0      .1       0   440.7    .045       0   455.7      .1       0
Bank Sta=440.7,455.7
XS Rating Curve= 0 ,0
Exp/Cntr=0.3,0.1

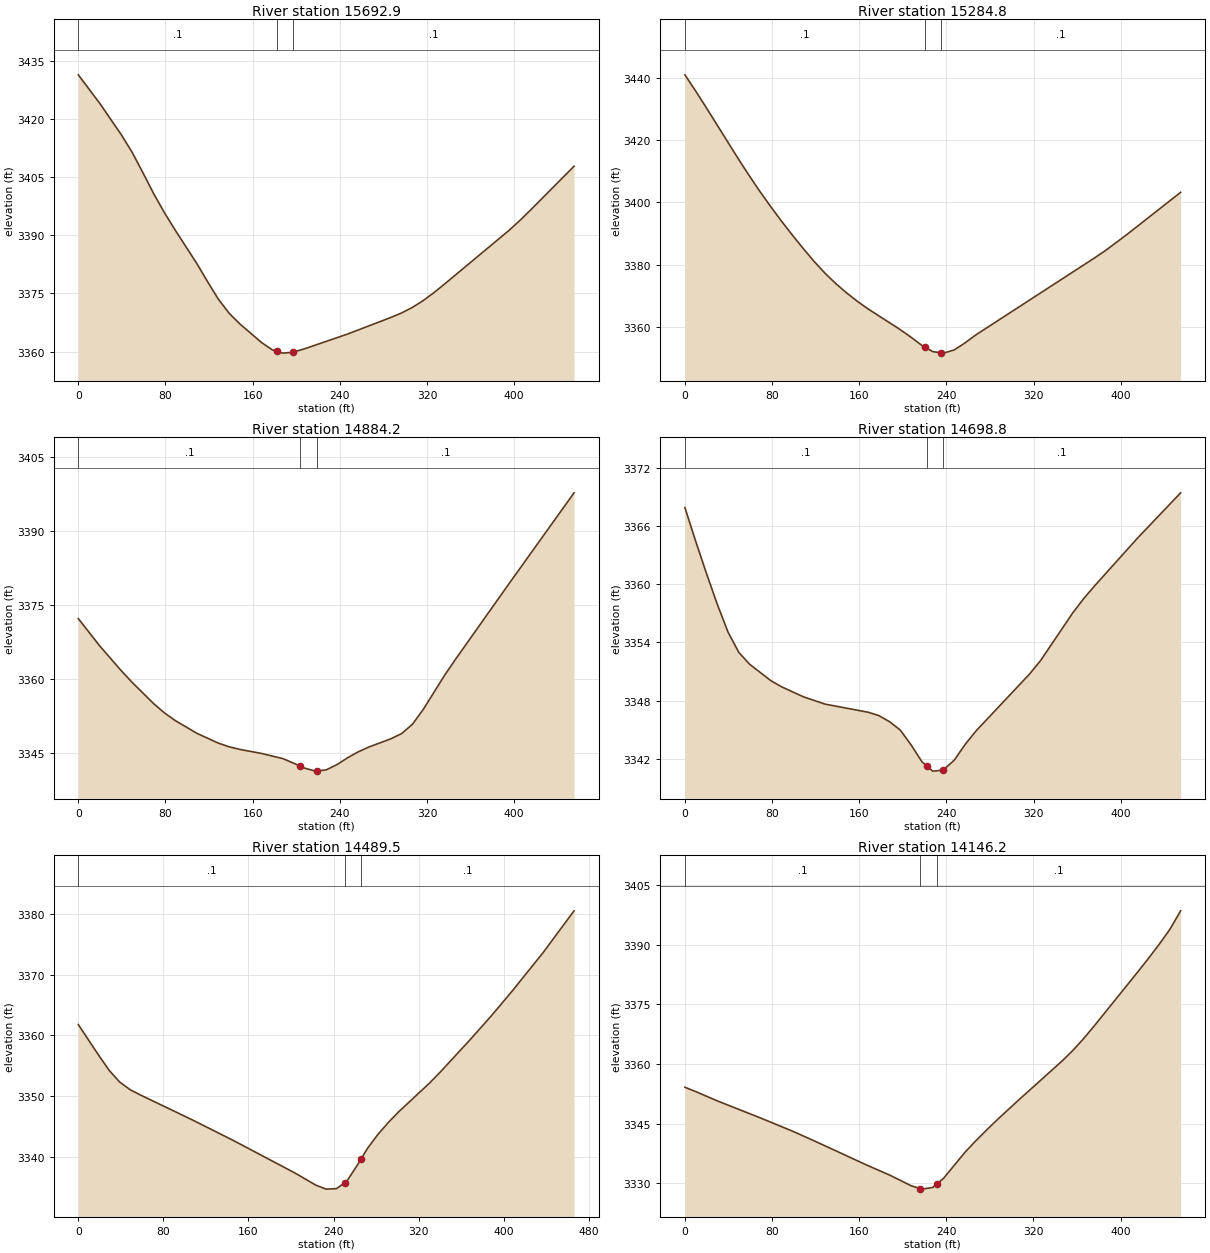
Type RM Length L Ch R = 1 ,15692.9 ,408.7,408.2,407.7
XS GIS Cut Line= 2
      2126111.03      402053.571     2126565.378      402077.922
#Sta/Elev= 30
       0 3431.41    19.8    3424    39.6 3415.89    49.5 3411.37    59.4 3406.09
    69.2 3400.72    79.1  3395.8      89  3391.3   108.8  3382.7   118.7    3378
   128.6 3373.49   138.5 3369.86   148.4  3367.1   168.2 3362.32     178 3360.44
   181.9 3360.11   187.9 3359.59   196.9 3359.82   207.7 3360.71   247.3 3364.53
   286.8 3368.79   296.7 3369.96   306.6 3371.39   316.5 3373.14   326.4  3375.2
   336.3 3377.45   395.6 3391.34   405.5 3393.89   415.4 3396.61     455 3407.83
#Mann= 3 , 0 , 0
       0      .1       0   181.9    .045       0   196.9      .1       0
Bank Sta=181.9,196.9
XS Rating Curve= 0 ,0
Exp/Cntr=0.3,0.1

Type RM Length L Ch R = 1 ,15284.8 ,400.5,400.5,400.5
XS GIS Cut Line= 3
     2126089.622      402452.997     2126316.796      402465.173
      2126543.97      402477.349
#Sta/Elev= 30
       0 3440.86     9.9 3435.66    19.8 3430.25    49.5 3413.69    59.4 3408.37
    69.2 3403.32    79.1 3398.48      89 3393.83    98.9  3389.4   108.8 3385.13
   118.7 3381.04   128.6  3377.3   138.5 3373.98   148.4    3371   158.3  3368.3
   168.2 3365.85   197.8 3359.19   207.7 3356.76   217.6 3354.15     220 3353.67
   227.5 3352.18     235 3351.81   237.4  3351.7   247.3 3352.74   257.2    3355
   267.1 3357.55   375.9 3382.18   385.8 3384.51   405.5 3389.65     455 3403.22
#Mann= 3 , 0 , 0
       0      .1       0     220    .045       0     235      .1       0
Bank Sta=220,235
XS Rating Curve= 0 ,0
Exp/Cntr=0.3,0.1

Type RM Length L Ch R = 1 ,14884.2 ,176.5,185.4,194.3
XS GIS Cut Line= 2
     2126068.214      402852.424     2126522.562      402876.776
#Sta/Elev= 30
       0 3372.19    19.8 3366.61    39.6 3361.58    49.5 3359.24    69.2 3354.94
    79.1 3353.06      89 3351.51   108.8 3348.93   128.6 3346.93   138.5 3346.19
   148.4 3345.66   168.2 3344.84   187.9 3343.79   203.9 3342.27   207.7 3341.87
   217.6 3341.26   218.9 3341.29   227.5 3341.51   237.4 3342.58   247.3 3343.99
   257.2  3345.2   267.1 3346.19   286.8 3347.81   296.7 3348.87   306.6 3350.75
   316.5 3353.74   336.3 3360.74   346.2 3363.94   395.6 3379.36     455  3397.7
#Mann= 3 , 0 , 0
       0      .1       0   203.9    .045       0   218.9      .1       0
Bank Sta=203.9,218.9
XS Rating Curve= 0 ,0
Exp/Cntr=0.3,0.1

Type RM Length L Ch R = 1 ,14698.8 ,210.7,209.3,208
XS GIS Cut Line= 2
      2126029.33       402942.74     2126439.978      403138.683
#Sta/Elev= 30
       0  3367.9     9.9 3364.43    19.8 3361.11    29.7 3357.94    39.6 3355.06
    49.5 3352.97    59.4 3351.75    79.1 3350.04      89 3349.41   108.8 3348.39
   128.6 3347.64   168.2  3346.8     178 3346.46   187.9 3345.82   197.8 3344.95
   207.7 3343.42   217.6 3341.69     222 3341.26   227.5 3340.73     237 3340.83
   247.3 3341.87   257.2 3343.48   267.1 3344.86   316.5 3350.76   326.4 3352.12
   356.1 3357.06     366 3358.51   375.9 3359.81   415.4 3364.75     455 3369.42
#Mann= 3 , 0 , 0
       0      .1       0     222    .045       0     237      .1       0
Bank Sta=222,237
XS Rating Curve= 0 ,0
Exp/Cntr=0.3,0.1

Type RM Length L Ch R = 1 ,14489.5 ,344,343.3,343.2
XS GIS Cut Line= 3
     2125887.981      403128.227     2126105.689        403211.3
     2126321.129      403300.417
#Sta/Elev= 27
       0  3361.8    19.4 3356.68    29.1 3354.24    38.8 3352.35    48.6 3351.09
    58.2 3350.22   106.8 3346.14   145.6 3342.73   203.9 3337.34   223.3 3335.36
     233  3334.7   242.7 3334.78   250.7 3335.76   252.4 3335.98   262.2 3338.59
   265.7 3339.61   271.9  3341.4   281.6 3343.68   291.3 3345.63     301 3347.39
   330.2 3352.15   339.9 3353.89     369 3359.41   388.4 3363.24   407.9 3367.29
     437 3373.63   466.2 3380.53
#Mann= 3 , 0 , 0
       0      .1       0   250.7    .045       0   265.7      .1       0
Bank Sta=250.7,265.7
XS Rating Curve= 0 ,0
Exp/Cntr=0.3,0.1

Type RM Length L Ch R = 1 ,14146.2 ,413.6,413.9,414.1
XS GIS Cut Line= 3
     2125705.674      403409.303     2125918.208      403490.402
     2126128.531      403577.401
#Sta/Elev= 28
       0 3354.17     9.9 3353.09    29.7 3350.75    69.2 3346.47    98.9 3343.11
   118.7 3340.69   168.1 3334.45   187.9 3332.09   207.7 3329.39     216 3328.68
   217.6 3328.54   227.5 3328.96     231 3329.77   237.4 3331.24   257.2 3337.84
   267.1 3340.71     277 3343.42   286.9 3346.04   306.6 3351.01   346.2 3360.76
   356.1 3363.42     366 3366.39   375.9 3369.64   415.5  3383.1   425.4 3386.53
   435.3  3390.1   445.2 3393.88   455.1 3398.56
#Mann= 3 , 0 , 0
       0      .1       0     216    .045       0     231      .1       0
Bank Sta=216,231
XS Rating Curve= 0 ,0
Exp/Cntr=0.3,0.1

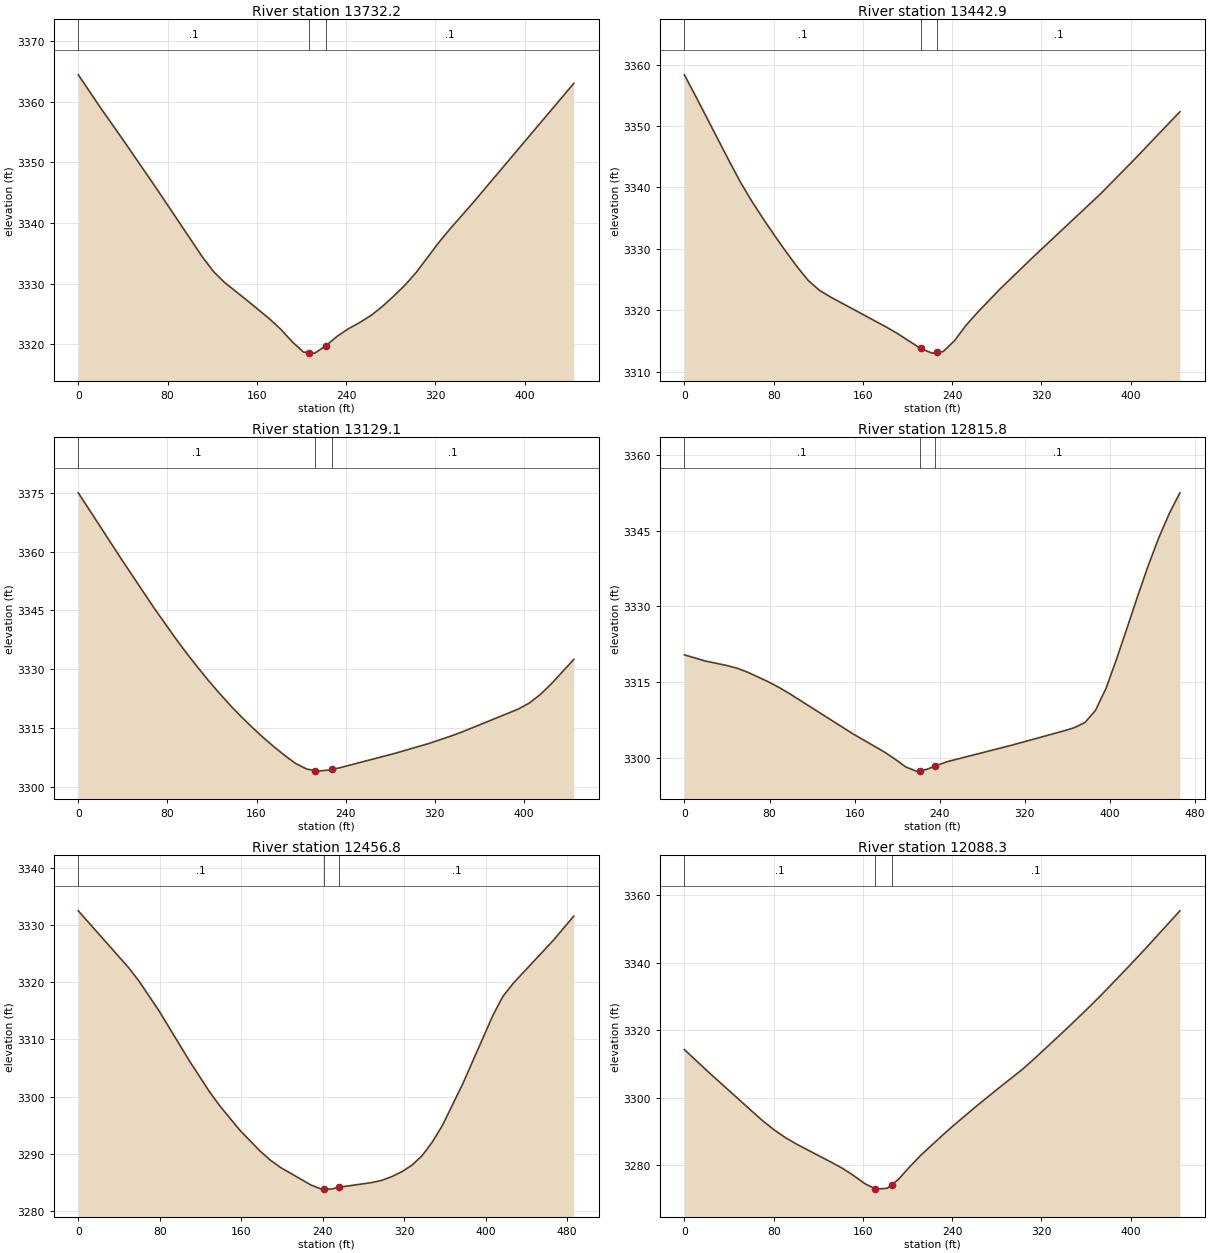
Type RM Length L Ch R = 1 ,13732.2 ,289.6,289.4,289.2
XS GIS Cut Line= 3
      2125459.29      403721.895      2125666.65      403801.019
     2125871.854      403885.902
#Sta/Elev= 27
       0 3364.45    20.2 3358.94    40.4 3353.64    70.6 3345.54     111 3334.44
   121.1    3332   131.2 3330.15   151.3 3327.21   171.5 3324.14   181.6 3322.42
   191.7 3320.38   201.8 3318.68   206.7  3318.6   211.8 3318.51   221.7 3319.69
     232  3321.3   242.1 3322.54   252.2 3323.57   262.3 3324.73   272.4  3326.2
   282.5  3327.9   292.6 3329.71   302.7 3331.81   322.9 3336.74     333 3338.99
   353.2 3343.23     444 3363.04
#Mann= 3 , 0 , 0
       0      .1       0   206.7    .045       0   221.7      .1       0
Bank Sta=206.7,221.7
XS Rating Curve= 0 ,0
Exp/Cntr=0.3,0.1

Type RM Length L Ch R = 1 ,13442.9 ,310.5,313.8,315.4
XS GIS Cut Line= 3
     2125382.201      403994.771      2125589.56      404073.895
     2125794.765      404158.778
#Sta/Elev= 26
       0 3358.32    10.1 3354.85    40.4  3344.2    50.4  3340.8    60.5 3337.72
    70.6 3334.91    80.7  3332.2    90.8  3329.6   100.9 3327.11     111 3324.85
   121.1 3323.24   131.2 3322.14   181.6 3317.21   191.7 3316.13   211.7 3313.79
   221.9 3313.03   226.7 3313.16     232  3313.3   242.1 3315.06   252.2 3317.52
   262.3 3319.58   282.5  3323.4   312.8 3328.72   373.4 3339.04   403.6 3344.62
     444 3352.31
#Mann= 3 , 0 , 0
       0      .1       0   211.7    .045       0   226.7      .1       0
Bank Sta=211.7,226.7
XS Rating Curve= 0 ,0
Exp/Cntr=0.3,0.1

Type RM Length L Ch R = 1 ,13129.1 ,328.9,313.2,298.7
XS GIS Cut Line= 3
     2125189.159      404192.152     2125383.914      404303.804
      2125580.62      404403.277
#Sta/Elev= 30
       0 3374.98      39 3357.93    68.3 3345.48    87.8 3337.65    97.6 3333.93
   107.4 3330.39   117.1    3327   126.9 3323.77   136.6  3320.7   146.4 3317.83
   156.2 3315.12   165.9 3312.57   175.7 3310.17   185.4 3307.96   195.2  3305.9
     205  3304.5   212.5 3304.09   214.7 3303.96   224.5 3304.21   227.5 3304.38
   234.5  3304.8   284.6 3308.52   314.7 3311.01   334.7 3312.92   344.7 3313.97
   394.8 3319.76   404.8 3321.31   414.9 3323.52   424.9 3326.28   444.9 3332.47
#Mann= 3 , 0 , 0
       0      .1       0   212.5    .045       0   227.5      .1       0
Bank Sta=212.5,227.5
XS Rating Curve= 0 ,0
Exp/Cntr=0.3,0.1

Type RM Length L Ch R = 1 ,12815.8 ,341.1,359,376.9
XS GIS Cut Line= 2
     2125149.143      404631.142     2125609.486      404560.671
#Sta/Elev= 30
       0 3320.43    19.8  3319.2    39.6 3318.33    49.5 3317.79    59.4    3317
    79.3 3315.05    89.2 3313.95    99.1 3312.72   158.5 3304.78   188.3 3301.16
   198.2 3299.75   208.1 3298.23     218 3297.41     221 3297.51   227.9 3297.76
     236 3298.46   247.7 3299.32   307.2 3302.52   356.7 3305.38   366.6 3306.02
   376.5 3307.04   386.4 3309.44   396.4 3313.85   406.2  3319.6   416.2 3325.82
   426.1 3332.09     436 3338.12   445.9 3343.61   455.8 3348.42   465.7  3352.5
#Mann= 3 , 0 , 0
       0      .1       0     221    .045       0     236      .1       0
Bank Sta=221,236
XS Rating Curve= 0 ,0
Exp/Cntr=0.3,0.1

Type RM Length L Ch R = 1 ,12456.8 ,383.7,368.5,353.4
XS GIS Cut Line= 2
     2124994.263      404704.995     2125391.476      404986.149
#Sta/Elev= 30
       0 3332.47    49.7 3322.48    59.6  3320.2    79.4 3314.96   109.2 3306.23
   129.1 3300.79     139 3298.39   158.9 3294.09   178.8 3290.45   188.7  3288.9
   198.6 3287.63   228.4 3284.58   238.4 3283.87   241.1 3283.87   248.3 3283.85
   256.1 3284.18     288 3284.99     298 3285.38   307.9 3286.04   317.8  3286.9
   327.7 3288.04   337.7 3289.71   347.6 3292.06   357.5 3294.95   377.4 3302.18
   407.2 3314.23   417.1 3317.55   427.1  3319.8   466.8 3327.38   486.6 3331.55
#Mann= 3 , 0 , 0
       0      .1       0   241.1    .045       0   256.1      .1       0
Bank Sta=241.1,256.1
XS Rating Curve= 0 ,0
Exp/Cntr=0.3,0.1

Type RM Length L Ch R = 1 ,12088.3 ,403.5,403.5,402.9
XS GIS Cut Line= 3
     2125054.994      405171.893     2125277.024      405169.098
     2125498.766      405160.139
#Sta/Elev= 30
       0 3314.33    20.2 3308.07    60.6 3296.04    70.6 3293.13    80.7 3290.48
    90.8  3288.2   100.9 3286.25   131.2 3281.04   141.3 3279.22   151.4 3277.08
   161.5 3274.66   170.6 3273.16   171.6    3273   181.7 3273.24   185.6 3274.27
   191.8 3275.89   201.9 3279.61     212 3283.09   232.1  3289.2   242.2 3292.14
   262.4 3297.76   282.6 3303.17   302.8 3308.43   312.8 3311.37   343.1 3320.66
   363.3 3327.09   373.4 3330.42   393.5  3337.3   413.7 3344.38     444 3355.39
#Mann= 3 , 0 , 0
       0      .1       0   170.6    .045       0   185.6      .1       0
Bank Sta=170.6,185.6
XS Rating Curve= 0 ,0
Exp/Cntr=0.3,0.1

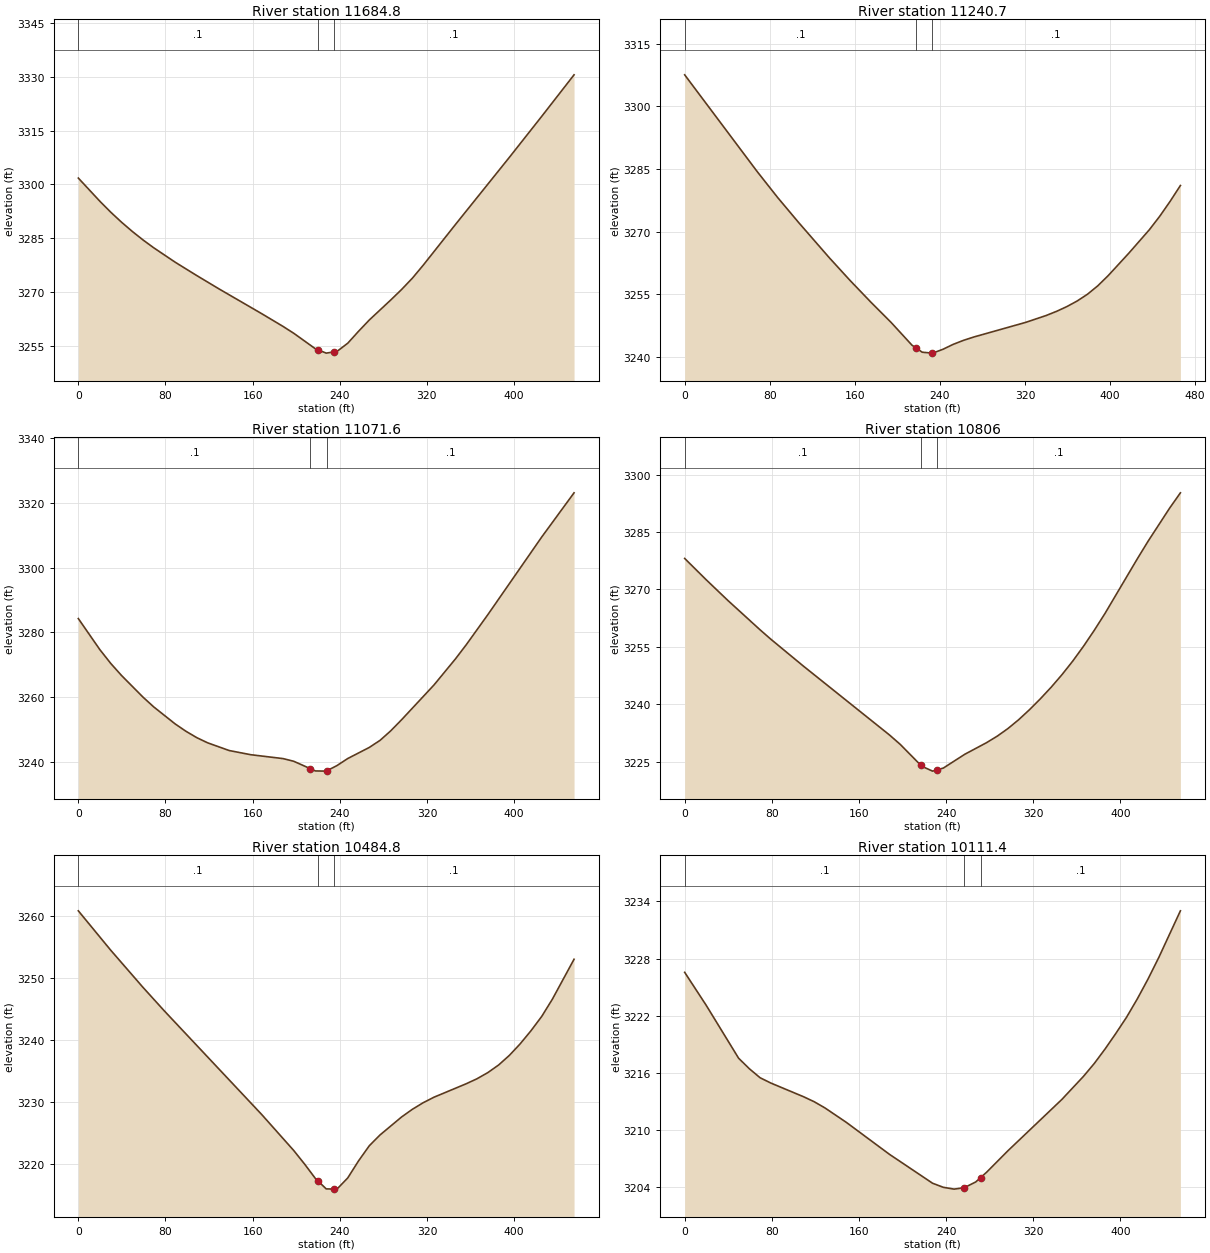
Type RM Length L Ch R = 1 ,11684.8 ,454.2,444,434.1
XS GIS Cut Line= 3
     2125060.029      405571.861     2125287.618      405568.996
     2125514.914      405559.813
#Sta/Elev= 29
       0 3301.74    19.8 3295.27    29.7 3292.24    39.6 3289.45    49.5 3286.87
    59.4 3284.48    69.3 3282.28    89.1 3278.24   108.9 3274.52   128.6 3270.93
   168.2 3263.95     188 3260.36   197.9 3258.43   217.7 3254.12   220.1 3253.83
   227.6 3252.92   235.1 3253.29   237.5  3253.4   247.4  3255.7   257.3 3259.02
   267.2 3262.18     287 3267.79   296.8 3270.67   306.7 3273.83   316.6 3277.43
   346.3 3288.82   395.7 3307.51   425.4 3318.94   455.1 3330.53
#Mann= 3 , 0 , 0
       0      .1       0   220.1    .045       0   235.1      .1       0
Bank Sta=220.1,235.1
XS Rating Curve= 0 ,0
Exp/Cntr=0.3,0.1

Type RM Length L Ch R = 1 ,11240.7 ,160,169.1,178.6
XS GIS Cut Line= 3
      2125055.36      406080.814     2125264.305      405977.335
     2125470.183      405868.148
#Sta/Elev= 30
       0 3307.56      68 3284.44    87.4 3278.17   106.9 3272.25     136 3263.73
   155.4 3258.32   174.9 3253.14   194.3 3248.18   213.7 3242.79   217.5 3242.13
   223.4 3241.09   232.5 3240.88   233.2 3240.87   242.9 3241.79   252.6 3242.98
   262.3 3243.94     272 3244.74   320.6 3248.23     340 3249.89   349.7 3250.88
   359.4 3252.02   369.1 3253.36   378.8 3254.98   388.5    3257   398.2 3259.42
   417.7 3264.82   437.1 3270.47   446.8 3273.68   456.5 3277.23   466.2 3281.04
#Mann= 3 , 0 , 0
       0      .1       0   217.5    .045       0   232.5      .1       0
Bank Sta=217.5,232.5
XS Rating Curve= 0 ,0
Exp/Cntr=0.3,0.1

Type RM Length L Ch R = 1 ,11071.6 ,265.4,265.6,265.7
XS GIS Cut Line= 2
     2125112.085      406143.242      2125566.16      406114.258
#Sta/Elev= 30
       0 3284.24    19.8 3274.61    29.7 3270.38    39.6 3266.64    59.4 3259.91
    69.2  3256.9      89  3251.6    98.9 3249.33   108.8 3247.37   118.7 3245.78
   138.5 3243.39   158.3  3242.1   187.9  3240.9   197.8 3240.06     213 3237.77
   217.6 3237.08   227.5 3237.02     228 3237.11   237.4 3238.74   247.3 3240.92
   267.1 3244.36     277 3246.56   286.8 3249.51   296.7 3252.92   326.4 3263.67
   346.2 3271.78   356.1 3276.16   375.9 3285.46   425.3 3309.47     455 3323.16
#Mann= 3 , 0 , 0
       0      .1       0     213    .045       0     228      .1       0
Bank Sta=213,228
XS Rating Curve= 0 ,0
Exp/Cntr=0.3,0.1

Type RM Length L Ch R = 1 ,10806   ,321.3,321.3,321.3
XS GIS Cut Line= 2
     2125055.988      406400.002     2125510.064      406371.019
#Sta/Elev= 30
       0 3278.11    19.8 3272.53    39.6 3267.15    69.2 3259.47    79.1 3257.01
   108.8 3250.03   187.9 3232.02   197.8 3229.56   216.7  3224.1   217.6 3223.84
   227.5 3222.56   231.7  3222.9   237.4 3223.36   257.2 3226.98     277 3229.98
   286.8 3231.68   296.7 3233.68   306.6    3236   316.5 3238.61   326.4 3241.43
   336.3 3244.45   346.2 3247.72   356.1 3251.27     366 3255.15   375.9 3259.32
   385.8 3263.75   415.4 3277.99   425.3 3282.59   445.1 3291.25     455 3295.25
#Mann= 3 , 0 , 0
       0      .1       0   216.7    .045       0   231.7      .1       0
Bank Sta=216.7,231.7
XS Rating Curve= 0 ,0
Exp/Cntr=0.3,0.1

Type RM Length L Ch R = 1 ,10484.8 ,385.8,373.3,360.8
XS GIS Cut Line= 3
     2125081.468      406719.783     2125308.506      406705.291
     2125535.544        406690.8
#Sta/Elev= 30
       0 3260.82    29.7 3254.47    59.4 3248.45    79.1 3244.63   168.2 3227.95
   197.8  3222.1   207.7 3219.92   217.6  3217.6     220 3217.19   227.5 3215.92
     235 3215.89   237.4 3215.88   247.3 3217.69   257.2 3220.44   267.1 3222.89
     277 3224.64   296.7 3227.53   306.6 3228.77   316.5 3229.83   326.4 3230.72
   356.1  3232.9     366 3233.71   375.9  3234.7   385.8 3235.93   395.6 3237.47
   405.5 3239.33   415.4 3241.44   425.3 3243.76   435.2 3246.58     455    3253
#Mann= 3 , 0 , 0
       0      .1       0     220    .045       0     235      .1       0
Bank Sta=220,235
XS Rating Curve= 0 ,0
Exp/Cntr=0.3,0.1

Type RM Length L Ch R = 1 ,10111.4 ,528.5,523.5,518.5
XS GIS Cut Line= 2
     2125247.979      407187.988     2125605.275      406906.272
#Sta/Elev= 29
       0 3226.55    19.8 3223.08    49.5 3217.53    59.4 3216.42    69.2 3215.48
    79.1 3214.92   108.8  3213.5   118.7 3212.97   128.6 3212.32   148.4 3210.79
   187.9 3207.44   227.5  3204.4   237.4 3203.97   247.3 3203.78   256.6 3203.93
   267.1 3204.53   271.6 3204.99     277 3205.54   296.7 3207.81   346.2  3213.2
     366 3215.62   375.9 3216.97   385.8 3218.49   395.6 3220.11   405.5 3221.82
   415.4 3223.75   425.3 3225.85   435.2 3228.12     455 3233.01
#Mann= 3 , 0 , 0
       0      .1       0   256.6    .045       0   271.6      .1       0
Bank Sta=256.6,271.6
XS Rating Curve= 0 ,0
Exp/Cntr=0.3,0.1

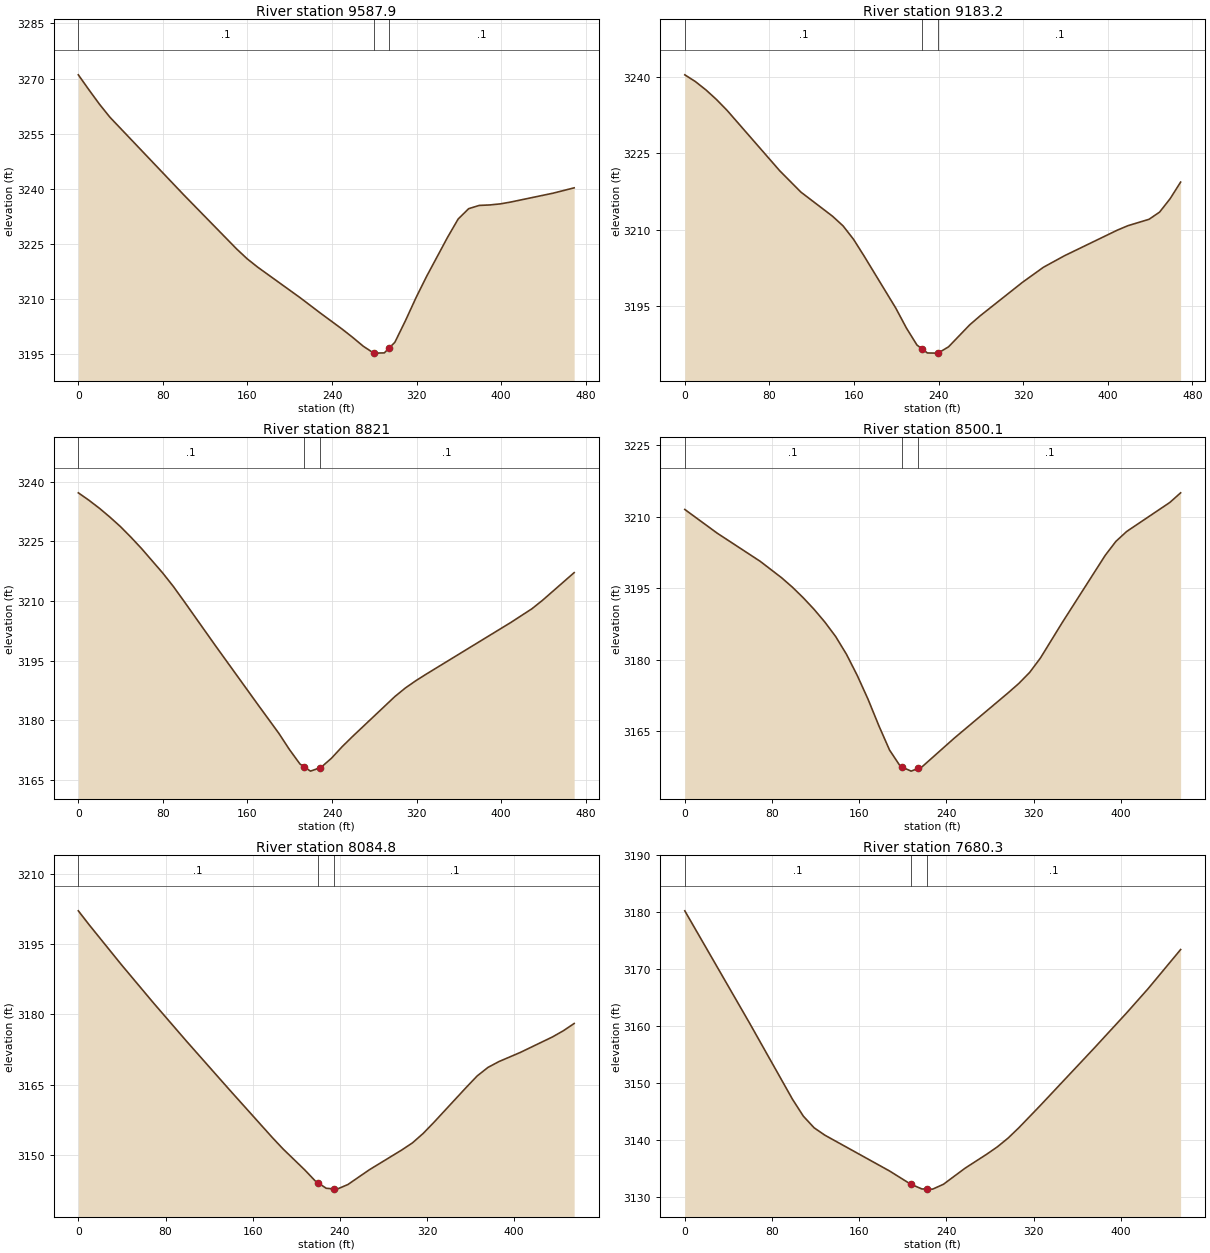
Type RM Length L Ch R = 1 ,9587.9  ,421.9,404.7,387.4
XS GIS Cut Line= 2
     2125668.393      407534.507     2125985.232      407188.641
#Sta/Elev= 30
       0 3271.01      10 3266.95      20 3263.02    29.9 3259.48    99.8 3238.36
   149.7 3223.69   159.7    3221   169.7 3218.72   209.6 3210.47   229.5 3206.13
   249.5  3201.9   259.5 3199.64   269.5 3197.24   279.3 3195.39   279.4 3195.36
   289.4 3195.42   294.3 3196.83   299.4  3198.3   309.4 3204.17   319.4 3210.42
   329.3 3216.15   349.3 3226.87   359.3 3231.82   369.2 3234.62   379.2 3235.51
   389.2 3235.64   399.2 3235.93   409.2 3236.44   449.1 3238.84     469 3240.29
#Mann= 3 , 0 , 0
       0      .1       0   279.3    .045       0   294.3      .1       0
Bank Sta=279.3,294.3
XS Rating Curve= 0 ,0
Exp/Cntr=0.3,0.1

Type RM Length L Ch R = 1 ,9183.2  ,347.1,362.2,377.2
XS GIS Cut Line= 2
     2126152.741      407725.471      2126159.63       407256.47
#Sta/Elev= 30
       0  3240.4      10 3239.08      20 3237.44    29.9 3235.57    39.9 3233.45
    89.8 3221.58   109.8  3217.4   139.7 3212.67   149.7 3210.77   159.7 3208.11
   169.7 3204.82   199.6 3194.63   209.6 3190.74   219.6  3187.4   224.6 3186.61
   229.5 3185.84   239.5 3185.81   239.6 3185.82   249.5 3187.05   269.5 3191.36
   279.4 3193.13   319.4  3199.7   339.3 3202.66   359.3 3204.93   409.2 3209.94
   419.2 3210.81   439.1 3212.06   449.1 3213.47   459.1 3216.11     469 3219.36
#Mann= 3 , 0 , 0
       0      .1       0   224.6    .045       0   239.6      .1       0
Bank Sta=224.6,239.6
XS Rating Curve= 0 ,0
Exp/Cntr=0.3,0.1

Type RM Length L Ch R = 1 ,8821    ,331.8,320.9,310.1
XS GIS Cut Line= 2
     2126307.937      407856.252     2126601.419      407490.358
#Sta/Elev= 30
       0 3237.22      10 3235.36      20 3233.32    29.9  3231.1    39.9  3228.7
    49.9 3226.01    59.9 3223.16    79.8 3217.04    89.8 3213.68    99.8 3209.99
   129.7 3198.74   169.7 3183.96   189.6  3176.7   199.6 3172.63   209.6 3168.97
   213.2 3168.31   219.6 3167.16   228.2 3167.96   229.5 3168.09   239.5 3170.42
   249.5  3173.3   259.5 3175.91   299.4 3185.93   309.4  3188.1   319.4 3189.95
   329.3 3191.61   409.2  3204.6   429.1 3208.04   439.1 3210.17     469 3217.13
#Mann= 3 , 0 , 0
       0      .1       0   213.2    .045       0   228.2      .1       0
Bank Sta=213.2,228.2
XS Rating Curve= 0 ,0
Exp/Cntr=0.3,0.1

Type RM Length L Ch R = 1 ,8500.1  ,398.9,415.4,431.8
XS GIS Cut Line= 2
     2126681.519      408011.567     2126766.344      407564.544
#Sta/Elev= 30
       0  3211.5    29.7 3206.53    69.2 3200.62      89 3197.14    98.9 3195.16
   108.8 3192.95   118.7 3190.53   128.6 3187.85   138.5 3184.82   148.4  3181.1
   158.3 3176.65   168.2 3171.66     178 3166.17   187.9 3161.02   197.8 3157.61
     199 3157.49   207.7  3156.6     214 3157.16   217.6 3157.48   247.3 3163.52
   296.7 3173.02   306.6 3175.01   316.5 3177.32   326.4 3180.35   346.2 3187.71
   385.8 3201.87   395.6  3204.8   405.5 3206.88   445.1 3212.97     455 3214.99
#Mann= 3 , 0 , 0
       0      .1       0     199    .045       0     214      .1       0
Bank Sta=199,214
XS Rating Curve= 0 ,0
Exp/Cntr=0.3,0.1

Type RM Length L Ch R = 1 ,8084.8  ,394.6,404.4,414.3
XS GIS Cut Line= 3
     2126858.337      408169.379     2127039.914      408032.317
     2127221.492      407895.255
#Sta/Elev= 28
       0 3202.13     9.9 3199.16    39.6 3190.61    69.2  3182.4    98.9  3174.4
   138.5 3163.98     178 3153.74   187.9 3151.29   207.7 3146.84   217.6 3144.42
     220 3144.05   227.5  3142.9     235 3142.76   237.4 3142.72   247.3 3143.69
   267.1 3146.86   296.7 3151.06   306.6 3152.59   316.5 3154.62   326.4    3157
   356.1 3164.47     366 3166.88   375.9  3168.7   385.8 3169.93   405.5 3171.89
   435.2 3175.22   445.1 3176.53     455 3178.08
#Mann= 3 , 0 , 0
       0      .1       0     220    .045       0     235      .1       0
Bank Sta=220,235
XS Rating Curve= 0 ,0
Exp/Cntr=0.3,0.1

Type RM Length L Ch R = 1 ,7680.3  ,484.1,474.6,465.1
XS GIS Cut Line= 2
     2127023.044      408429.578     2127468.176       408335.33
#Sta/Elev= 22
       0 3180.27    59.4 3160.54    98.9 3147.11   108.8 3144.16   118.7 3142.11
   128.6 3140.81   187.9 3134.52   207.2 3132.21   217.6 3131.36   222.2 3131.35
   227.5 3131.33   237.4 3132.19   257.2 3135.01     277 3137.46   286.8 3138.76
   296.7 3140.31   306.6 3142.13   326.4 3146.07   375.9 3156.17   405.5 3162.33
   425.3 3166.61     455 3173.46
#Mann= 3 , 0 , 0
       0      .1       0   207.2    .045       0   222.2      .1       0
Bank Sta=207.2,222.2
XS Rating Curve= 0 ,0
Exp/Cntr=0.3,0.1