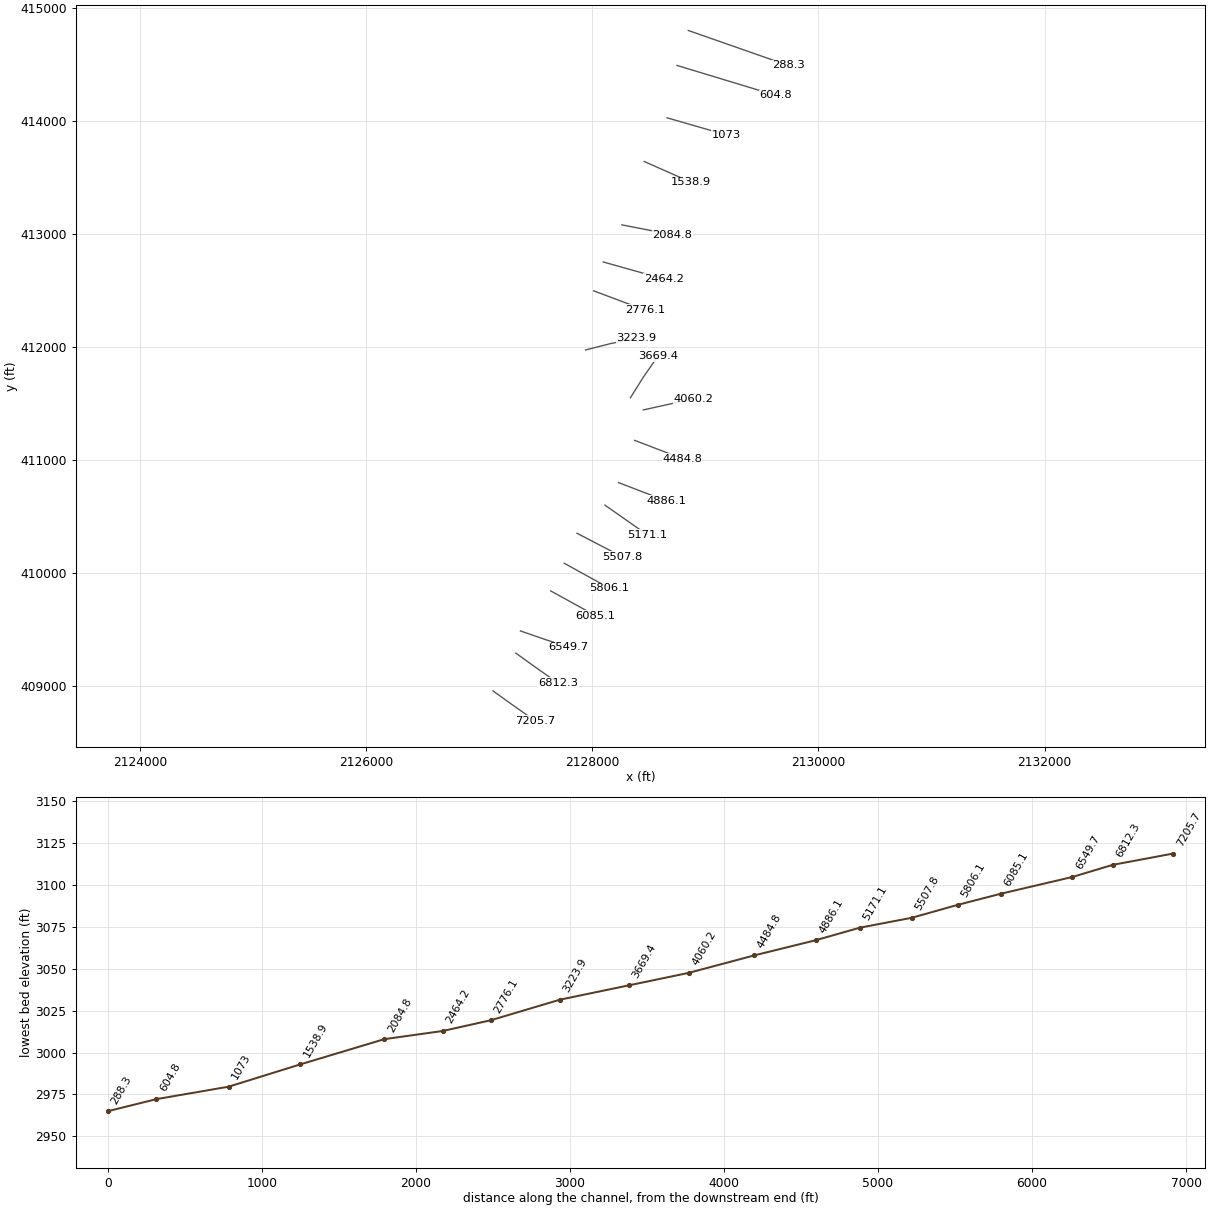
HEC-RAS study CldKnobFrk.prj: CldKnobFrk

--- CldKnobFrk.g01 (geometry) --- (continued)

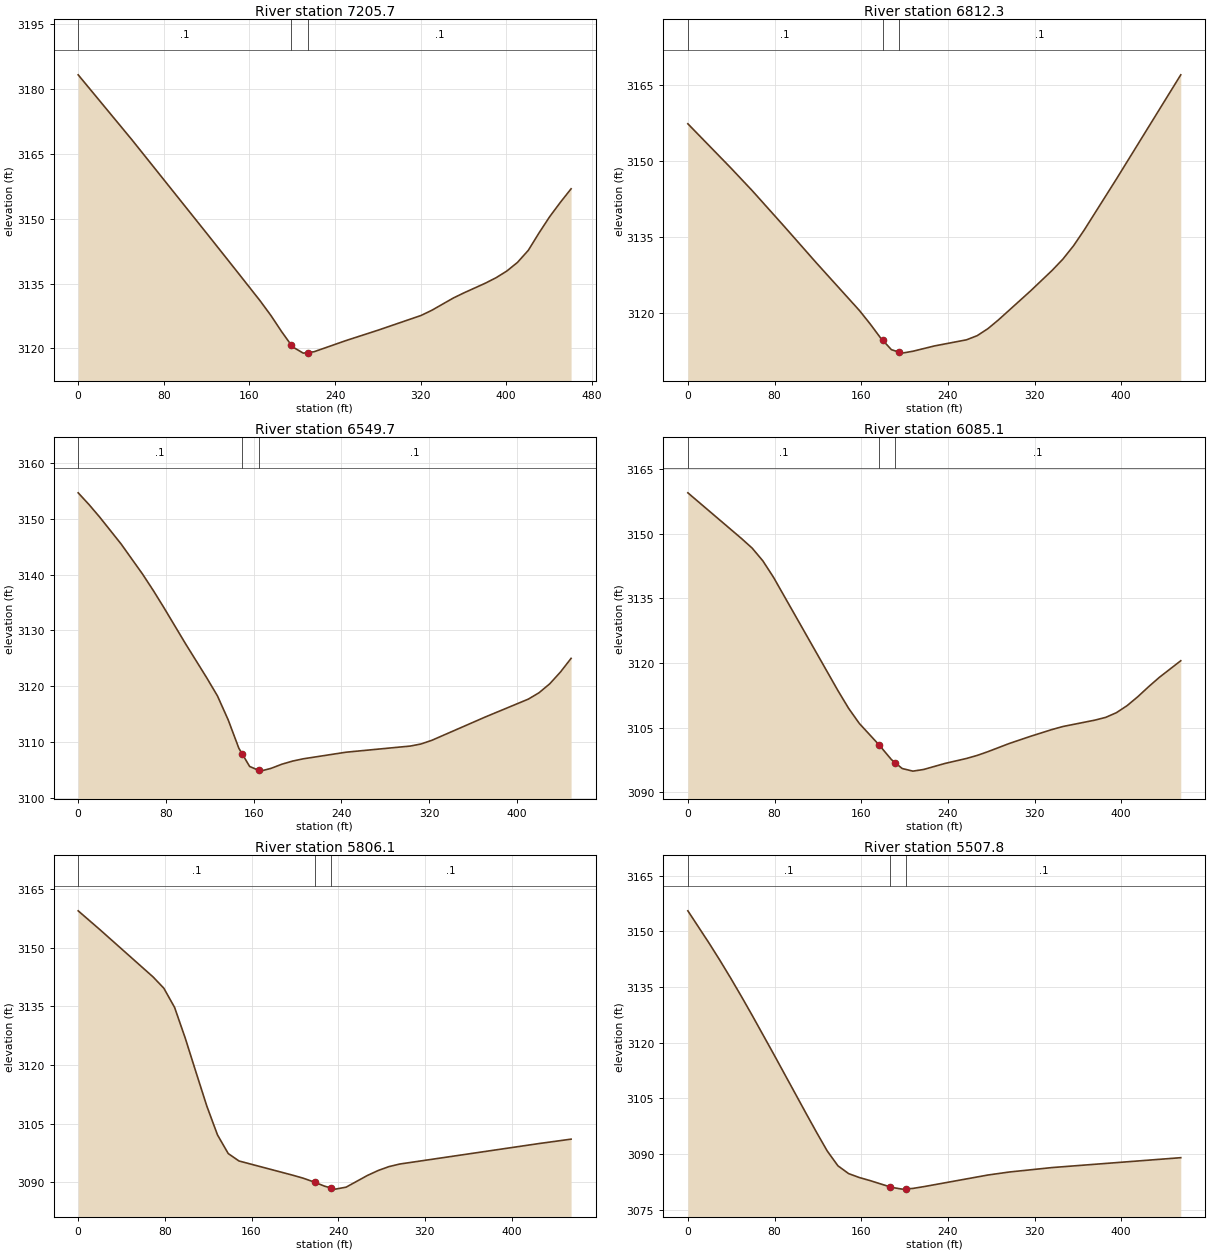
Type RM Length L Ch R = 1 ,7205.7  ,393.3,393.4,393.4
XS GIS Cut Line= 3
      2127121.29       408956.62     2127308.328      408822.272
     2127497.251      408690.531
#Sta/Elev= 27
       0 3183.27    50.1 3168.28   120.2 3146.58   150.2 3137.22   170.2 3130.94
   180.2 3127.57   190.2 3123.84   199.3  3120.7   200.2 3120.37   210.3  3118.9
   214.3 3119.02   220.3 3119.21   250.3 3121.81   280.4 3124.22   320.4 3127.61
   330.4  3128.8   350.5 3131.64   360.5 3132.84   380.5 3135.08   390.5 3136.34
   400.5 3137.88   410.5 3139.88   420.6 3142.67   430.6 3146.68   440.6 3150.46
   450.6 3153.78   460.6 3156.91
#Mann= 3 , 0 , 0
       0      .1       0   199.3    .045       0   214.3      .1       0
Bank Sta=199.3,214.3
XS Rating Curve= 0 ,0
Exp/Cntr=0.3,0.1

Type RM Length L Ch R = 1 ,6812.3  ,255.9,262.6,269.4
XS GIS Cut Line= 3
     2127323.766       409290.32     2127508.536      409157.601
     2127695.167      409027.458
#Sta/Elev= 25
       0 3157.29    39.6 3148.61    59.4 3144.13      89 3137.08   118.7 3129.89
   158.3 3120.55   168.2 3117.91     178  3115.1   179.7 3114.71   187.9 3112.82
   194.7 3112.35   197.8 3112.14   207.7 3112.51   227.5 3113.55   257.2 3114.76
   267.1 3115.58     277 3116.96   286.8  3118.7   316.5 3124.42   336.3 3128.44
   346.2 3130.65   356.1  3133.3     366 3136.42   395.7 3146.45     455 3166.93
#Mann= 3 , 0 , 0
       0      .1       0   179.7    .045       0   194.7      .1       0
Bank Sta=179.7,194.7
XS Rating Curve= 0 ,0
Exp/Cntr=0.3,0.1

Type RM Length L Ch R = 1 ,6549.7  ,468.4,464.6,460.8
XS GIS Cut Line= 3
     2127364.426      409486.718       2127576.8      409413.314
     2127790.209      409342.874
#Sta/Elev= 30
       0 3154.59     9.8 3152.51    19.5 3150.28    39.1 3145.46    58.6  3140.1
    68.4 3137.17    78.2 3134.07    97.7 3127.69   117.2 3121.55     127 3118.31
   136.8 3114.02   146.5 3108.96   149.4 3108.01   156.3 3105.72   164.4 3105.03
   166.1 3104.88   175.8 3105.37   185.6 3106.11   195.4 3106.67   205.2 3107.08
   244.2 3108.26   302.9 3109.36   312.6 3109.73   322.4 3110.38   371.3 3114.56
   410.4 3117.74   420.1 3118.87   429.9 3120.47   439.7 3122.58   449.4 3125.02
#Mann= 3 , 0 , 0
       0      .1       0   149.4    .045       0   164.4      .1       0
Bank Sta=149.4,164.4
XS Rating Curve= 0 ,0
Exp/Cntr=0.3,0.1

Type RM Length L Ch R = 1 ,6085.1  ,278.9,279,279.1
XS GIS Cut Line= 2
     2127631.322      409841.327     2128029.769      409621.634
#Sta/Elev= 30
       0 3159.49    49.5 3148.88    59.4 3146.64    69.2  3143.7    79.1 3139.86
   138.5 3113.58   148.4 3109.45   158.3 3105.93   176.5 3100.96   187.9 3097.55
   191.5  3096.8   197.8 3095.48   207.7 3094.87   217.6 3095.25   237.4 3096.66
   257.2 3097.81   267.1 3098.52     277 3099.39   296.7 3101.29   316.5 3102.97
   336.3 3104.54   346.2 3105.23   375.9 3106.72   385.8 3107.36   395.6 3108.44
   405.5 3110.08   415.4 3112.16   425.3 3114.47   435.2 3116.64     455  3120.5
#Mann= 3 , 0 , 0
       0      .1       0   176.5    .045       0   191.5      .1       0
Bank Sta=176.5,191.5
XS Rating Curve= 0 ,0
Exp/Cntr=0.3,0.1

Type RM Length L Ch R = 1 ,5806.1  ,297.8,298.3,298.8
XS GIS Cut Line= 2
     2127751.497       410085.41     2128149.944      409865.717
#Sta/Elev= 24
       0  3159.4    19.8 3154.65    69.2 3142.48    79.1  3139.6      89  3134.7
    98.9 3126.79   108.8  3118.1   118.7 3109.51   128.6  3102.1   138.5 3097.34
   148.4 3095.44   197.8 3091.82   207.7 3091.04   218.3    3090   227.5 3088.99
   233.3 3088.55   237.4 3088.24   247.3 3088.74   267.1 3091.75     277 3093.01
   286.8 3093.99   296.7 3094.65   425.3 3099.89     455 3101.02
#Mann= 3 , 0 , 0
       0      .1       0   218.3    .045       0   233.3      .1       0
Bank Sta=218.3,233.3
XS Rating Curve= 0 ,0
Exp/Cntr=0.3,0.1

Type RM Length L Ch R = 1 ,5507.8  ,340.1,336.7,333.2
XS GIS Cut Line= 3
     2127864.678      410350.645     2128066.552      410245.748
     2128268.425      410140.851
#Sta/Elev= 24
       0 3155.49    19.8 3146.69    29.7  3142.1    39.6 3137.33    49.5 3132.39
    59.4 3127.32    79.1 3116.96   108.8 3101.09   118.7 3095.87   128.6 3090.82
   138.5 3086.81   148.4  3084.7   158.3 3083.64   168.2 3082.82   186.8 3081.11
   187.9    3081   197.8 3080.52   201.8 3080.59   207.7 3080.71   217.6 3081.18
     277 3084.32   296.7 3085.13   336.3 3086.33     455 3088.99
#Mann= 3 , 0 , 0
       0      .1       0   186.8    .045       0   201.8      .1       0
Bank Sta=186.8,201.8
XS Rating Curve= 0 ,0
Exp/Cntr=0.3,0.1

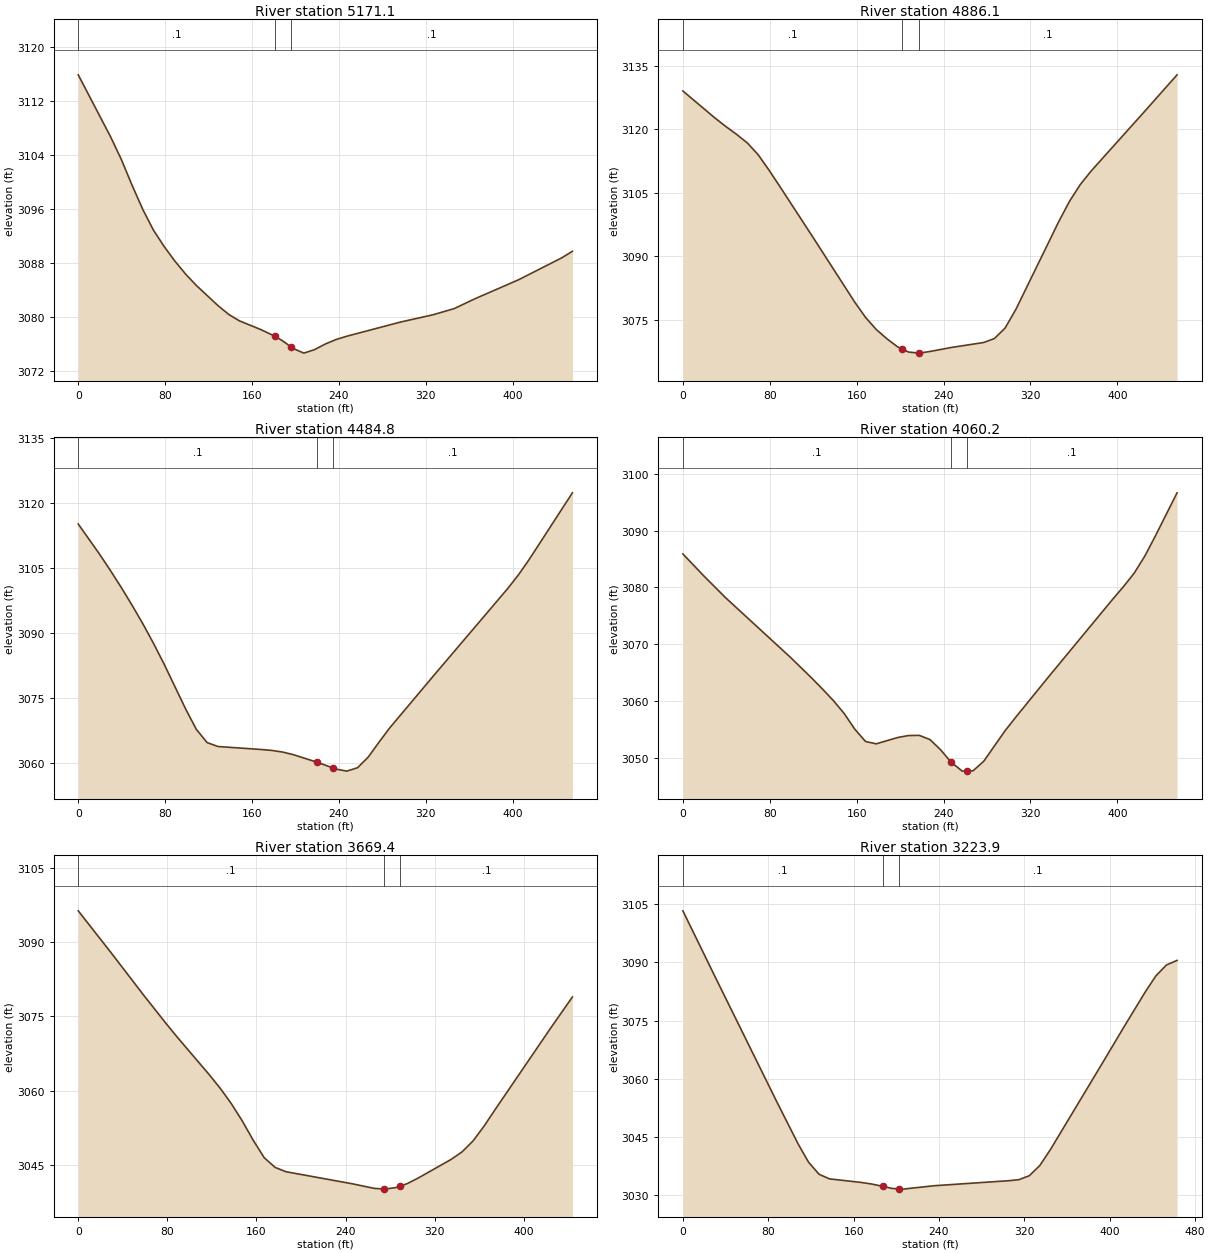
Type RM Length L Ch R = 1 ,5171.1  ,279.4,285,290.6
XS GIS Cut Line= 2
     2128111.788      410599.344     2128484.505      410338.371
#Sta/Elev= 30
       0 3115.91    29.7 3106.74    39.6 3103.38    49.5 3099.55    59.4 3095.95
    69.2 3092.88    79.1 3090.44      89 3088.27    98.9 3086.34   108.8 3084.65
   128.6 3081.68   138.5 3080.37   148.4 3079.41   168.2 3078.11   181.3 3077.11
   187.9 3076.47   196.3  3075.5   197.8 3075.32   207.7 3074.62   217.6 3075.14
   227.5 3075.97   237.4 3076.64   247.3 3077.13   296.7 3079.23   326.4  3080.3
   346.2 3081.23     366 3082.74   405.5 3085.51   445.1 3088.75     455 3089.73
#Mann= 3 , 0 , 0
       0      .1       0   181.3    .045       0   196.3      .1       0
Bank Sta=181.3,196.3
XS Rating Curve= 0 ,0
Exp/Cntr=0.3,0.1

Type RM Length L Ch R = 1 ,4886.1  ,401.4,401.4,401.3
XS GIS Cut Line= 2
     2128231.352      410799.075     2128656.169      410636.116
#Sta/Elev= 30
       0 3129.05    29.7 3122.64    39.6 3120.66    49.5  3118.8    59.4 3116.77
    69.2 3114.04    79.1 3110.44      89 3106.62   118.7 3094.94   158.3 3079.18
   168.2 3075.59     178 3072.75   187.9 3070.54   197.8 3068.62     202 3068.12
   207.7 3067.42     217 3067.18   217.6 3067.16   227.5 3067.55   247.3  3068.5
     277 3069.67   286.8  3070.6   296.7 3073.09   306.6 3077.49   346.2 3098.28
   356.1 3103.07     366    3107   375.9 3110.16   425.3 3124.28     455 3132.87
#Mann= 3 , 0 , 0
       0      .1       0     202    .045       0     217      .1       0
Bank Sta=202,217
XS Rating Curve= 0 ,0
Exp/Cntr=0.3,0.1

Type RM Length L Ch R = 1 ,4484.8  ,411.4,424.6,437.8
XS GIS Cut Line= 3
     2128374.612       411172.54     2128587.021      411091.061
     2128799.429      411009.581
#Sta/Elev= 29
       0 3115.13    19.8 3108.09    29.7 3104.36    39.6 3100.47    49.5 3096.39
    59.4 3092.12    69.2  3087.6    79.1 3082.74    98.9 3072.39   108.8 3067.66
   118.7 3064.63   128.6 3063.73   168.2 3063.04     178 3062.83   187.9 3062.46
   197.8 3061.86     220 3060.09     235 3058.73   237.4 3058.51   247.3 3058.04
   257.2 3058.83   267.1 3061.32     277 3064.75   286.8 3068.03   326.4 3079.85
   395.6 3100.27   405.5 3103.45   415.4 3107.01     455 3122.33
#Mann= 3 , 0 , 0
       0      .1       0     220    .045       0     235      .1       0
Bank Sta=220,235
XS Rating Curve= 0 ,0
Exp/Cntr=0.3,0.1

Type RM Length L Ch R = 1 ,4060.2  ,374.1,390.7,407.4
XS GIS Cut Line= 2
     2128450.857      411441.612     2128895.008      411540.378
#Sta/Elev= 30
       0 3085.88    19.8 3081.91    39.6 3078.12    98.9 3067.69   118.7    3064
   128.6 3062.07   138.5 3060.06   148.4  3057.8   158.3 3055.01   168.2 3052.84
     178 3052.43   197.8 3053.54   207.7 3053.89   217.6 3053.92   227.5 3053.18
   237.4 3051.36   246.7 3049.24   257.2 3047.62   261.7 3047.64   267.1 3047.67
     277 3049.36   296.7 3054.75   306.6 3057.15   336.3 3064.14   395.6 3077.87
   405.5 3080.09   415.4 3082.46   425.3  3085.5   435.2 3089.11     455 3096.65
#Mann= 3 , 0 , 0
       0      .1       0   246.7    .045       0   261.7      .1       0
Bank Sta=246.7,261.7
XS Rating Curve= 0 ,0
Exp/Cntr=0.3,0.1

Type RM Length L Ch R = 1 ,3669.4  ,461.3,445.6,429.8
XS GIS Cut Line= 3
     2128336.916      411549.164     2128451.658      411732.246
     2128581.736      411919.018
#Sta/Elev= 28
       0 3096.31    29.5 3087.85    58.9 3079.24    78.6 3073.64    88.4 3070.94
   117.8 3063.19   127.7 3060.42   137.5 3057.37   147.3 3053.89   157.1    3050
     167 3046.47   176.8 3044.51   186.6 3043.64   245.8 3041.22   265.6 3040.29
   274.3 3040.15   275.4 3040.13   285.3 3040.45   289.3 3040.76   295.2 3041.22
   305.1 3042.35   334.8 3046.13   344.7 3047.67   354.6 3049.89   364.5 3052.89
   374.4 3056.22   423.9 3072.55   443.7 3078.92
#Mann= 3 , 0 , 0
       0      .1       0   274.3    .045       0   289.3      .1       0
Bank Sta=274.3,289.3
XS Rating Curve= 0 ,0
Exp/Cntr=0.3,0.1

Type RM Length L Ch R = 1 ,3223.9  ,461.5,447.8,434
XS GIS Cut Line= 3
     2127940.058      411971.902      2128158.81      412027.756
     2128391.316      412075.246
#Sta/Elev= 25
       0 3103.31    29.4 3086.75    88.3 3053.95     108 3043.24   117.8 3038.53
   127.6 3035.43   137.4 3034.24   166.9 3033.33   176.7 3032.93   187.5 3032.31
   196.3 3031.77   202.5 3031.67   206.1  3031.6   235.7 3032.48   304.9 3033.76
   314.8 3034.03   324.6 3035.05   334.5 3037.69   344.4 3041.78   393.9 3064.42
   413.6 3073.51   433.4 3082.45   443.3 3086.56   453.2 3089.37   463.1 3090.53
#Mann= 3 , 0 , 0
       0      .1       0   187.5    .045       0   202.5      .1       0
Bank Sta=187.5,202.5
XS Rating Curve= 0 ,0
Exp/Cntr=0.3,0.1

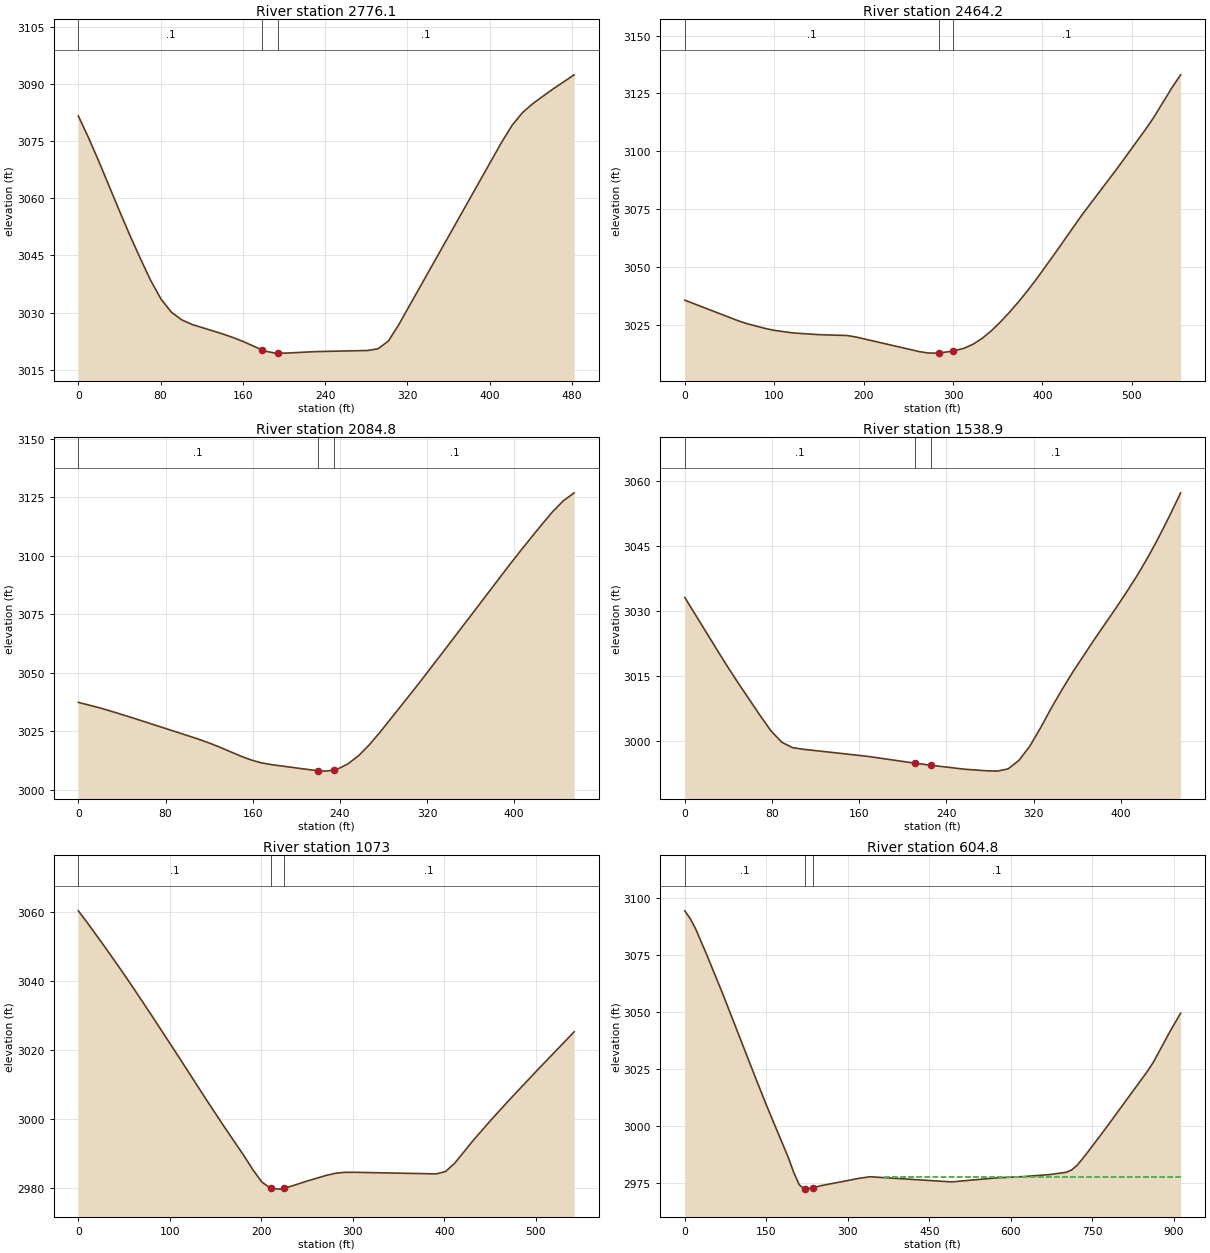
Type RM Length L Ch R = 1 ,2776.1  ,310.4,311.9,313.3
XS GIS Cut Line= 2
      2128012.36      412494.717     2128464.043      412325.503
#Sta/Elev= 30
       0 3081.64      10 3075.88    20.1 3069.61    40.2 3056.57    50.2 3050.26
    60.3 3044.22    70.3 3038.47    80.4 3033.55    90.4 3030.13   100.5  3028.1
   110.5 3026.88   140.7 3024.36   150.7 3023.42   160.8 3022.35   178.9 3020.14
   180.9 3019.91   190.9 3019.37   193.9 3019.36     201 3019.34   231.1 3019.74
   281.4 3020.03   291.4 3020.48   301.5 3022.48   311.5 3026.73     412 3074.85
     422 3079.21   432.1 3082.54   442.1  3084.9   462.2 3088.82   482.3 3092.45
#Mann= 3 , 0 , 0
       0      .1       0   178.9    .045       0   193.9      .1       0
Bank Sta=178.9,193.9
XS Rating Curve= 0 ,0
Exp/Cntr=0.3,0.1

Type RM Length L Ch R = 1 ,2464.2  ,377.7,379.5,381.3
XS GIS Cut Line= 2
       2128096.3      412750.387     2128630.089      412600.397
#Sta/Elev= 30
       0 3035.78    60.5 3026.78    70.6 3025.52    90.7 3023.51   100.8 3022.71
     121 3021.63   151.2 3020.87   181.5 3020.53   191.5 3019.87   262.1 3013.59
   272.2 3012.98   282.3 3012.92   284.6    3013   299.6 3013.78   312.5 3015.04
   322.6 3016.81   332.7 3019.34   342.8 3022.56   352.8 3026.31   362.9 3030.47
     373 3034.97   383.1 3039.76   393.2 3044.84   413.3 3055.61   443.6 3072.29
   483.9 3092.84   514.1 3108.88   524.2 3114.52   544.4 3127.27   554.5 3133.06
#Mann= 3 , 0 , 0
       0      .1       0   284.6    .045       0   299.6      .1       0
Bank Sta=284.6,299.6
XS Rating Curve= 0 ,0
Exp/Cntr=0.3,0.1

Type RM Length L Ch R = 1 ,2084.8  ,550.9,545.8,540.8
XS GIS Cut Line= 3
     2128261.465      413078.536     2128484.752       413034.96
      2128708.04      412991.383
#Sta/Elev= 30
       0 3037.42    19.8 3035.06    29.7  3033.7    49.5 3030.85   108.8 3021.94
   118.7  3020.3   128.6  3018.5   148.4 3014.57   158.3 3012.84   168.2 3011.54
     178 3010.76   217.6 3008.31     220 3008.24   227.5 3008.03     235 3008.61
   237.4  3008.8   247.3  3011.1   257.2 3014.64   267.1 3019.32     277 3024.76
   306.6 3042.04   316.5 3047.95   336.3 3059.94   395.6 3096.14   405.5 3102.02
   415.4 3107.77   425.3 3113.42   435.2  3118.9   445.1 3123.59     455 3126.98
#Mann= 3 , 0 , 0
       0      .1       0     220    .045       0     235      .1       0
Bank Sta=220,235
XS Rating Curve= 0 ,0
Exp/Cntr=0.3,0.1

Type RM Length L Ch R = 1 ,1538.9  ,462.8,465.9,469
XS GIS Cut Line= 2
     2128459.298      413638.934     2128875.193      413454.392
#Sta/Elev= 30
       0  3033.1    29.7 3020.95    39.6 3016.96    49.5 3013.14    69.2 3005.79
    79.1 3002.27      89 2999.64    98.9 2998.38   108.8 2998.01   168.2 2996.36
   210.8 2994.81   225.8 2994.32   257.2 2993.39     277 2993.04   286.8 2992.96
   296.7 2993.48   306.6 2995.44   316.5 2998.68   326.4 3002.94   336.3 3007.53
   346.2 3011.82   356.1 3015.89   375.9 3023.42   395.6 3030.63   405.5 3034.38
   415.4 3038.29   425.3 3042.54   435.2 3047.15   445.1 3052.08     455 3057.28
#Mann= 3 , 0 , 0
       0      .1       0   210.8    .045       0   225.8      .1       0
Bank Sta=210.8,225.8
XS Rating Curve= 0 ,0
Exp/Cntr=0.3,0.1

Type RM Length L Ch R = 1 ,1073    ,468.5,468.2,467.9
XS GIS Cut Line= 2
      2128660.97      414025.306     2129181.525      413875.315
#Sta/Elev= 30
       0 3060.45      10 3056.94    30.1 3049.56    50.2 3041.93    60.2 3038.01
    80.3 3029.98   110.4 3017.74   140.4 3005.38   160.5  2997.3   180.6 2989.47
   190.6  2985.3   200.6 2981.65     210 2979.91   210.7 2979.78   220.7 2979.62
     225 2979.92   230.7 2980.31   250.8 2982.04   270.9 2983.61   280.9 2984.22
   290.9  2984.5     301 2984.51   391.2 2984.05   401.3 2984.76   411.3 2987.18
   431.4 2993.77   451.4 2999.86   471.5 3005.71   501.6 3014.22   541.7 3025.31
#Mann= 3 , 0 , 0
       0      .1       0     210    .045       0     225      .1       0
#XS Ineff= 2 , 0
                          310.57         2983.87
Permanent Ineff=
       F       F
Bank Sta=210,225
XS Rating Curve= 0 ,0
Exp/Cntr=0.3,0.1

Type RM Length L Ch R = 1 ,604.8   ,317.2,316.5,315.8
XS GIS Cut Line= 2
     2128749.199      414488.512     2129622.673      414223.822
#Sta/Elev= 30
       0  3094.5      10 3091.09    20.1  3086.5    40.1 3075.37    70.2 3057.81
   130.4 3020.99   150.4 3009.02   190.6 2986.03   200.6 2979.51   210.6 2974.11
   220.4 2972.24   220.6  2972.2   235.4  2972.8   250.7 2973.72     321 2976.95
     341 2977.64   491.4 2975.38   571.7  2977.1   621.8 2977.69     672  2978.6
   702.1  2979.6   712.1 2980.62   722.1 2982.68   732.2 2985.53   742.2 2988.62
   772.3  2998.1   852.5 3024.29   862.6 3028.03   892.6 3041.23   912.7 3049.55
#Mann= 3 , 0 , 0
       0      .1       0   220.4    .045       0   235.4      .1       0
#XS Ineff= 2 , 0
                          368.94         2977.43
Permanent Ineff=
       F       F
Bank Sta=220.4,235.4
XS Rating Curve= 0 ,0
Exp/Cntr=0.3,0.1

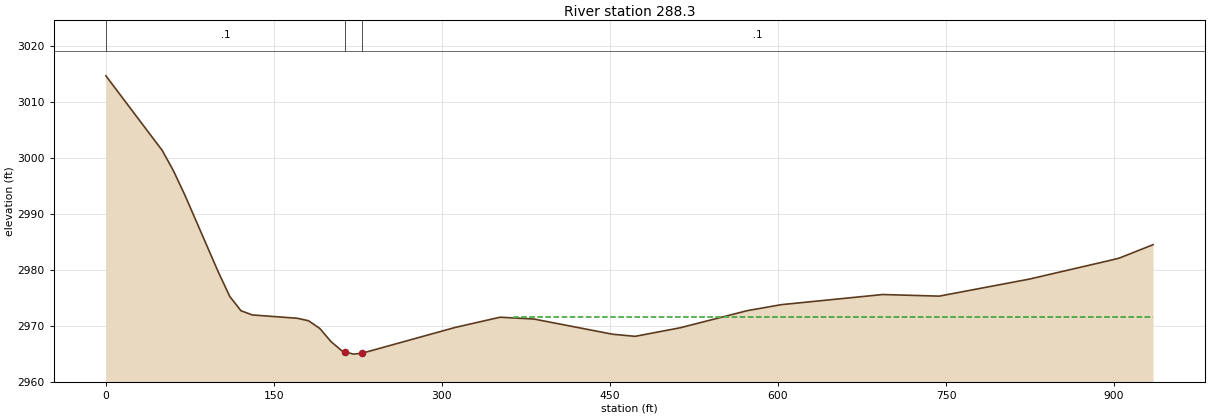
Type RM Length L Ch R = 1 ,288.3   ,282.8,288.3,293.8
XS GIS Cut Line= 2
     2128849.279      414797.678     2129731.576      414488.875
#Sta/Elev= 30
       0 3014.73    50.3 3001.38    60.3 2997.75    70.4 2993.45   100.5 2979.58
   110.6 2975.27   120.6 2972.72   130.7 2971.97   170.9 2971.37   180.9 2970.93
     191 2969.54     201 2967.19   211.1 2965.48   213.8 2965.34   221.1 2964.96
   228.8 2965.13   311.6 2969.72   351.8 2971.56     382 2971.24   452.3 2968.52
   472.4 2968.14   512.6 2969.67   572.9 2972.75   603.1 2973.81   693.5 2975.62
   743.8 2975.33   824.2 2978.37   894.6 2981.64   904.6 2982.13   934.8 2984.53
#Mann= 3 , 0 , 0
       0      .1       0   213.8    .045       0   228.8      .1       0
#XS Ineff= 2 , 0
                          364.52         2971.62
Permanent Ineff=
       F       F
Bank Sta=213.8,228.8
XS Rating Curve= 0 ,0
Exp/Cntr=0.3,0.1

Chan Stop Cuts=-1
Use User Specified Reach Order=0